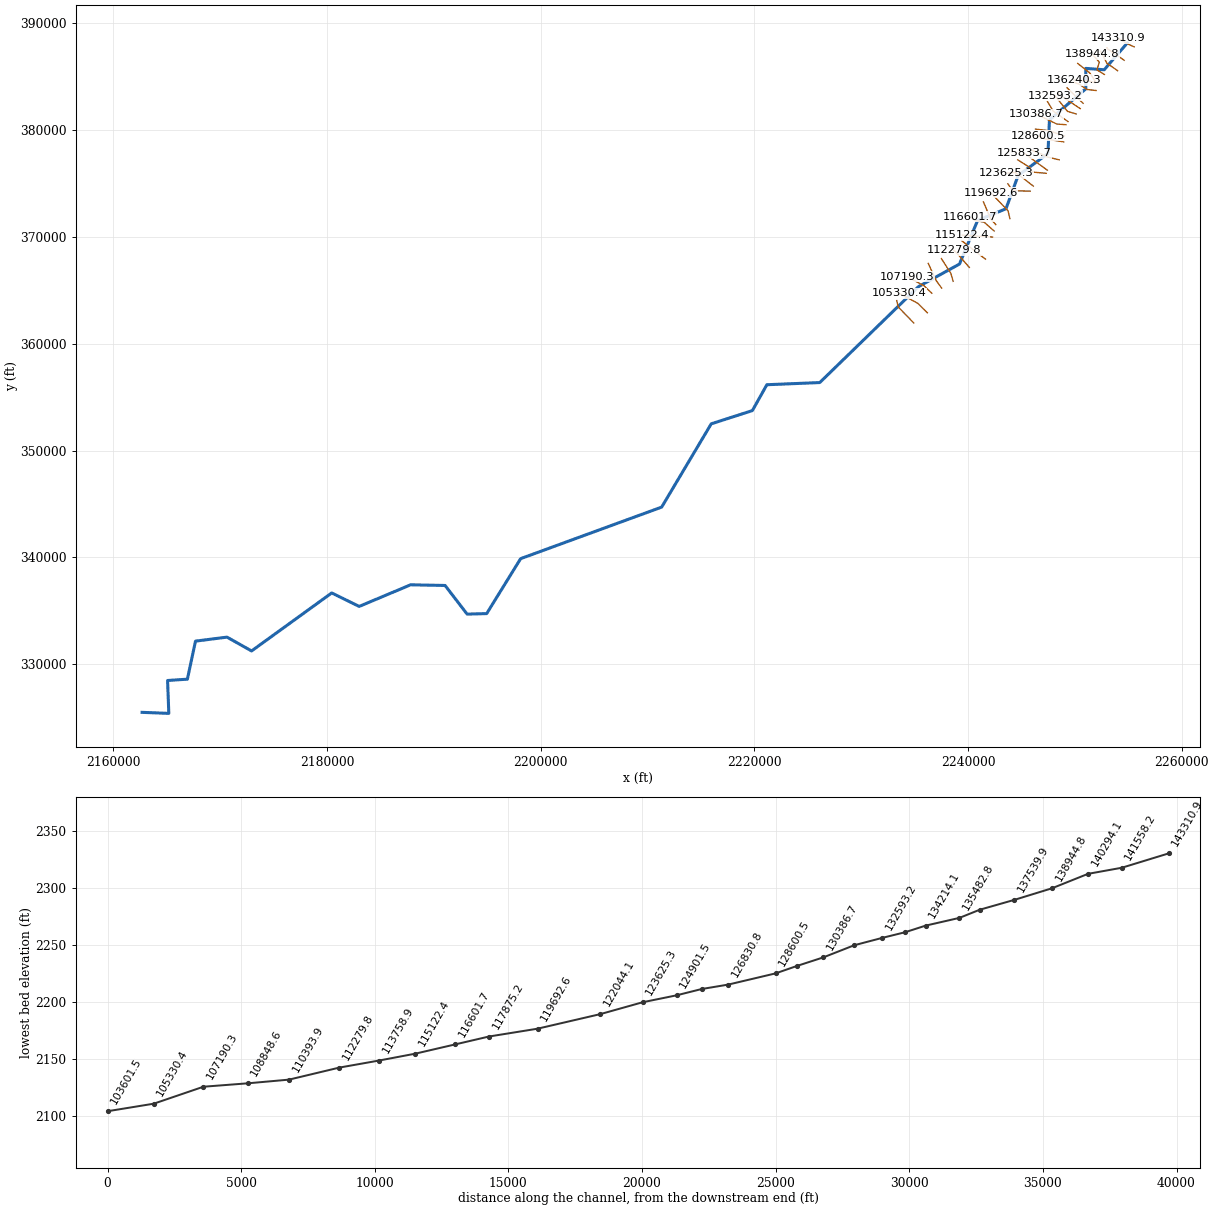
--- AntCk.prj (project) ---

Proj Title=AntCk
Current Plan=p01
Default Exp/Contr=0,0
English Units
Geom File=g01
Flow File=f01
Plan File=p01
BEGIN DESCRIPTION:
END DESCRIPTION:
DSS Export Rating Curves= 0
DSS Export Rating Curve Sorted= 0
DSS Export Volume Flow Curves= 0
DXF OffsetX= 0
DXF OffsetY= 0
DXF ScaleX= 0
DXF ScaleY= 0

--- AntCk.p01 (plan) ---

Plan Title=Floodplain
Program Version=4.00
Geom File=g01
Flow File=f01
K Sum by GR=0
Std Step Tol=0.01
Critical Tol=0.01
Num of Std Step Trials=20
Max Error Tol=0.3
Flow Tol Ratio=0.001
Split Flow NTrial=30
Split Flow Tol=0.02
Split Flow Ratio=0.02
Log Output Level=0
Friction Slope Method=1
Unsteady Friction Slope Method=2
Unsteady Bridges Friction Slope Method=1
Global Log Level=0
CheckData=False
Run HTab=0
Run UNet=0
Run PostProcess=0
UNET Theta=0
UNET Theta Warmup=0
UNET ZTol=0
UNET ZSATol=0
UNET MxIter=0
UNET MaxInSteps=0
UNET DtIC=0
UNET DtMin=0
UNET MaxCRTS=0
UNET WFStab=0
UNET SFStab=0
UNET WFX=0
UNET SFX=0
UNET DSS MLevel=0
UNET DZMax Abort=0
UNET Convert EG Bridges=0
UNET Use Existing IB Tables=0
UNET Froude Limit=0
UNET Froude Power=0
Write IC File=0
Echo Input=False
Echo Output=False
Write Detailed=0

--- AntCk.f01 (steady flow) ---

Flow Title=NFF Regression Equation
Program Version=4.00
Number of Profiles=1
Profile Names=P100yr
River Rch & RM=AntCk,Main      ,143310.9
1309.656
River Rch & RM=AntCk,Main      ,140294.1
1408.753
River Rch & RM=AntCk,Main      ,138944.8
1556.593
River Rch & RM=AntCk,Main      ,136240.3
1664.034
River Rch & RM=AntCk,Main      ,135482.8
1801.632
River Rch & RM=AntCk,Main      ,133448.4
1935.161
River Rch & RM=AntCk,Main      ,129407
2120.377
River Rch & RM=AntCk,Main      ,128600.5
2255.945
River Rch & RM=AntCk,Main      ,125833.7
2469.586
River Rch & RM=AntCk,Main      ,119692.6
2741.582
River Rch & RM=AntCk,Main      ,113758.9
3040.235
River Rch & RM=AntCk,Main      ,110393.9
3373.194
River Rch & RM=AntCk,Main      ,107190.3
3468.635
River Rch & RM=AntCk,Main      ,105330.4
3684.197
River Rch & RM=AntCk,Main      ,98683.9
3981.313
River Rch & RM=AntCk,Main      ,93858
4405.449
River Rch & RM=AntCk,Main      ,72164.9
10305.96
River Rch & RM=AntCk,Main      ,57370.8
11309.22
River Rch & RM=AntCk,Main      ,50725.9
11773.62
River Rch & RM=AntCk,Main      ,47127.3
12491.67
River Rch & RM=AntCk,Main      ,44599
13350.24
River Rch & RM=AntCk,Main      ,36805.7
14759.02
River Rch & RM=AntCk,Main      ,1325.2
16187.40
Boundary for River Rch & Prof#=AntCk,Main      ,1
Up Type=0
Dn Type=3
Dn Slope=0.004905

--- AntCk.g01 (geometry) ---

Geom Title=USGS 10m DEM
Program Version=4.10

River Reach=AntCk           ,Main
Reach XY= 30
     2254892.733      388141.041     2252741.692      385642.778
     2251010.789      385769.514     2251015.997      383858.055
     2247615.395      380946.918     2247472.594      377792.083
     2244687.872      375755.625     2243543.775      372628.889
     2240892.733      371543.819     2239194.816      367457.014
     2235344.122      365335.486     2226114.955      356363.264
     2221163.566      356160.138     2219807.664         353740.
     2215956.969      352500.417     2211316.344      344704.843
     2198116.692      339880.191     2194936.136      334736.093
     2193106.058      334688.513     2191043.449      337369.882
     2187820.005      337432.318     2183002.297      335409.749
     2180432.853      336670.166      2172929.38      331241.346
     2170631.379      332534.101     2167681.116      332159.749
     2166922.436      328598.985     2165068.269      328475.721
     2165182.853      325397.596     2162676.545      325493.458

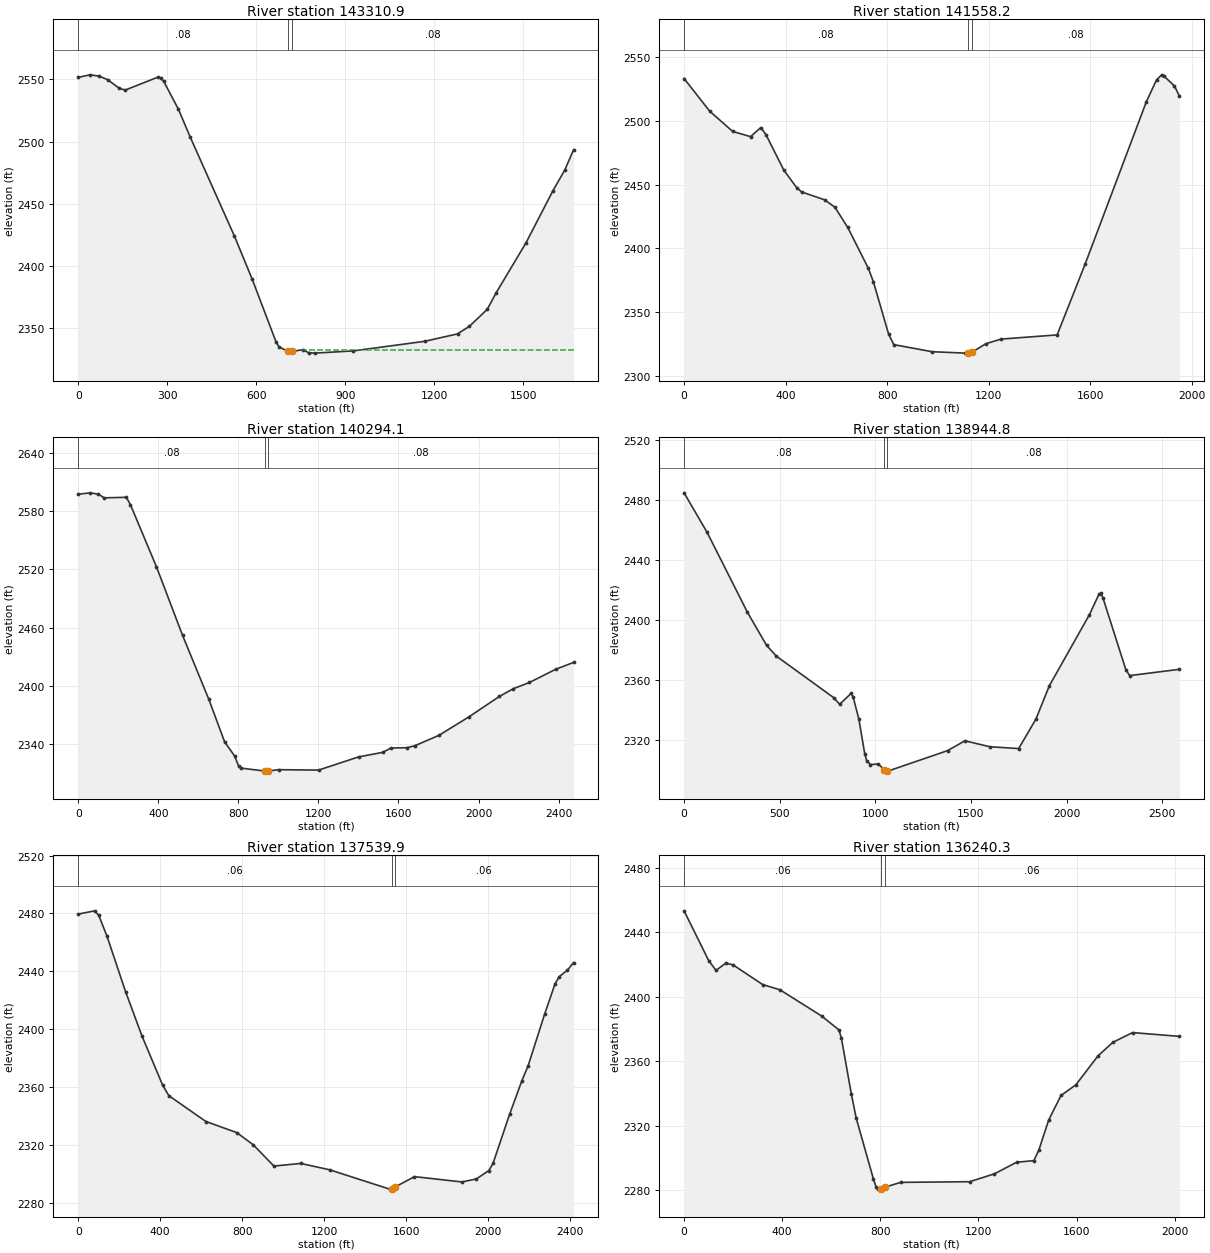
Type RM Length L Ch R = 1 ,143310.9,1728.1,1752.5,1761.9
XS GIS Cut Line= 3
     2255537.265      387786.699     2254985.181      388036.699
     2254073.723      388583.574
#Sta/Elev= 30
       0 2551.58    39.7 2553.63    69.6 2552.67    99.4 2549.72   139.1 2542.66
     159 2541.43   268.2 2551.73   278.2 2551.06   288.1 2548.38   337.8 2525.95
   377.5 2503.59   526.6 2423.99   586.2 2389.56   666.2 2339.38   676.2 2335.23
   706.4 2331.61   721.4  2331.6   756.5  2332.9   776.5  2330.5   796.6 2330.16
   926.9 2331.95  1167.6 2339.66  1277.9  2345.6    1318 2351.69  1378.2 2365.35
  1408.3 2378.68  1508.5 2418.66  1598.8 2460.31  1638.9 2477.02    1669 2493.45
#Mann= 3 , 0 , 0
       0     .08       0   706.4    .045       0   721.4     .08       0
#XS Ineff= 2 , 0
                          749.41         2332.86
Permanent Ineff=
       F       F
Bank Sta=706.4,721.4
XS Rating Curve= 0 ,0
Exp/Cntr=0.3,0.1

Type RM Length L Ch R = 1 ,141558.2,1288.4,1264,1254.1
XS GIS Cut Line= 3
     2254611.491      386528.537     2253762.319       387107.92
     2253006.025      387638.652
#Sta/Elev= 30
       0 2533.29   100.8 2507.66   191.5 2491.72     262 2487.65   302.4 2494.79
   322.5 2489.25   393.1 2461.31   443.4  2447.6   463.6 2444.16   554.3 2437.97
   594.6 2432.11     645 2416.27   725.6 2384.39   745.8  2373.7   806.3 2332.25
   826.4 2324.26   977.6  2318.7  1108.3 2317.59  1120.5 2317.84  1135.5 2318.43
  1188.7 2324.94  1248.9 2328.62  1469.9  2331.9  1580.4 2387.66  1821.4 2515.08
  1861.6 2532.27  1881.6 2536.19  1891.7 2535.04  1931.8 2527.48  1951.9 2519.42
#Mann= 3 , 0 , 0
       0     .08       0  1120.5    .045       0  1135.5     .08       0
Bank Sta=1120.5,1135.5
XS Rating Curve= 0 ,0
Exp/Cntr=0.3,0.1

Type RM Length L Ch R = 1 ,140294.1,1379.8,1349.3,1319.2
XS GIS Cut Line= 4
     2253993.305      385552.789      2253477.75       385917.86
     2253003.989      386233.701     2252410.425      387360.927
#Sta/Elev= 30
       0  2597.1    60.2 2598.56   100.3 2597.16   130.4 2593.41   240.7 2593.96
   260.7 2586.52   391.1 2522.48   521.4 2451.94   651.7 2386.64   731.6 2342.35
   781.6 2327.74   801.5 2317.47   811.5 2315.42   934.8 2312.27   941.4 2312.25
   949.8 2312.39  1001.3 2313.74  1201.1 2313.31  1401.7 2326.95  1522.1 2331.57
  1562.2 2336.03  1642.5 2336.35  1682.6  2338.4    1803 2349.14  1953.4 2368.24
  2103.9 2389.04  2174.1 2397.06  2254.4 2403.44  2384.8 2416.96  2475.1 2424.09
#Mann= 3 , 0 , 0
       0     .08       0   934.8    .045       0   949.8     .08       0
Bank Sta=934.8,949.8
XS Rating Curve= 0 ,0
Exp/Cntr=0.3,0.1

Type RM Length L Ch R = 1 ,138944.8,1377,1404.7,1432.5
XS GIS Cut Line= 4
     2252758.077      385204.271     2252062.201      385625.459
     2252281.719      386348.402     2251615.634      387122.454
#Sta/Elev= 30
       0 2485.03   120.5 2458.67   331.4 2405.38   431.8 2383.31     482 2376.25
   783.3 2348.44   813.4 2344.09   873.9  2351.5   883.9 2349.02   914.2 2334.02
   944.4 2311.26   954.4 2306.64   974.6 2303.97  1014.9 2304.32  1047.5 2300.51
  1062.5 2299.63  1065.3 2299.59  1377.6 2313.25  1468.2  2319.8    1599 2315.83
  1749.2 2314.62  1839.3 2334.19  1909.4 2356.41  2119.6 2403.92  2169.6 2417.58
  2179.7 2417.95  2189.7 2415.13  2309.8 2367.14  2329.8 2363.25  2590.1 2367.43
#Mann= 3 , 0 , 0
       0     .08       0  1047.5    .045       0  1062.5     .08       0
Bank Sta=1047.5,1062.5
XS Rating Curve= 0 ,0
Exp/Cntr=0.3,0.1

Type RM Length L Ch R = 1 ,137539.9,1285.7,1299.1,1312.6
XS GIS Cut Line= 3
     2251929.435       384522.13     2251389.216      385346.193
     2250262.135      386230.118
#Sta/Elev= 30
       0 2479.51    80.4 2481.77   100.6 2478.57   140.8 2464.14   231.3  2425.9
   311.7 2395.14   412.2  2361.3   442.4 2354.04   623.4 2336.18   774.2  2328.5
   854.6 2320.05   955.2  2305.4  1086.2 2307.22  1227.4 2302.81    1520 2289.46
  1530.2 2289.75  1545.2 2290.82    1641 2298.09    1873 2294.42  1943.6 2296.53
  2004.1 2302.32  2024.3 2307.17    2105 2341.03  2165.5 2364.45  2195.8 2374.72
  2276.5 2410.45  2326.9 2431.22  2347.1 2436.23  2387.4 2440.73  2417.7 2446.05
#Mann= 3 , 0 , 0
       0     .06       0  1530.2    .045       0  1545.2     .06       0
Bank Sta=1530.2,1545.2
XS Rating Curve= 0 ,0
Exp/Cntr=0.3,0.1

Type RM Length L Ch R = 1 ,136240.3,769.9,757.5,745.1
XS GIS Cut Line= 3
     2251906.545      384421.411     2251338.902      384585.648
     2249913.764      384684.377
#Sta/Elev= 30
       0 2453.44   100.2 2422.61   130.2 2416.48   170.3 2421.02   200.3 2419.87
   320.5 2407.68   390.6 2404.48   560.9 2388.16   631.2 2379.58   641.2 2374.53
   681.5  2340.1   701.6 2324.88     772 2286.97   782.1 2282.42   792.1 2280.79
     804 2281.13     819 2281.99   882.7 2284.98  1164.4  2285.4    1265 2290.28
  1355.5 2297.46  1425.9 2298.47    1446 2304.92  1486.3 2323.66  1536.6 2338.92
    1597 2345.48  1687.5 2363.49  1747.8 2371.83  1828.3 2377.91  2019.5 2375.54
#Mann= 3 , 0 , 0
       0     .06       0     804    .045       0     819     .06       0
Bank Sta=804,819
XS Rating Curve= 0 ,0
Exp/Cntr=0.3,0.1

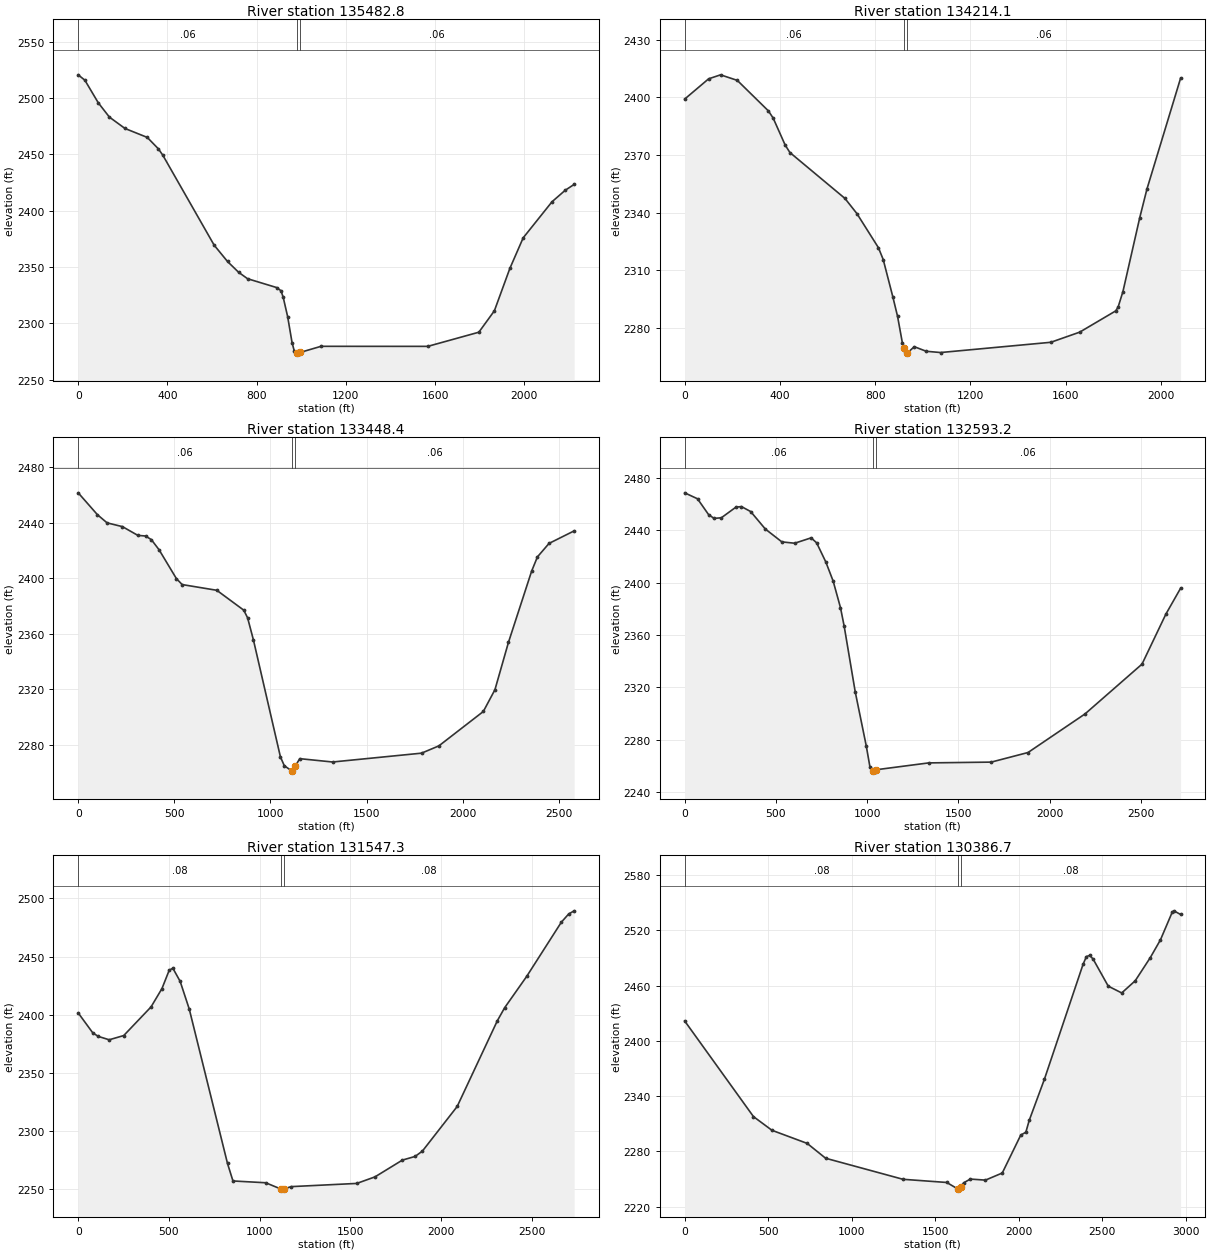
Type RM Length L Ch R = 1 ,135482.8,1273.1,1268.5,1263.8
XS GIS Cut Line= 4
     2251978.877      383695.342     2251096.238      383802.695
     2250436.609      384269.153     2249948.192      384466.152
#Sta/Elev= 30
       0 2520.58      30 2515.77    89.9 2495.77   139.9 2483.06   209.8 2472.98
   309.7 2465.05   359.6 2454.89   379.6 2449.18   609.4 2369.49   669.4 2354.97
   719.3 2345.38   759.3 2339.68   889.1 2331.88   909.1 2329.04   919.1 2323.24
     939  2306.1     959 2282.83   968.9 2275.51   978.9 2273.66   979.4 2273.67
   994.4 2274.23  1088.6  2279.7  1567.4 2279.66  1796.4 2292.22    1866 2311.21
  1935.5 2348.85  1995.1 2375.93  2124.3 2407.93  2183.9  2418.2  2223.7 2423.35
#Mann= 3 , 0 , 0
       0     .06       0   979.4    .045       0   994.4     .06       0
Bank Sta=979.4,994.4
XS Rating Curve= 0 ,0
Exp/Cntr=0.3,0.1

Type RM Length L Ch R = 1 ,134214.1,761.3,765.4,769.5
XS GIS Cut Line= 3
     2250765.088      382508.859     2249765.542      383455.332
     2249261.346      383950.682
#Sta/Elev= 30
       0 2399.06   100.5 2409.59   150.7 2411.68     221 2408.79   351.7 2392.91
   371.8 2389.15     422 2375.17   442.1 2371.24   673.2 2347.37   723.4 2339.49
   813.9 2321.72     834 2315.56   874.2 2296.26   894.3 2285.99   914.4 2272.28
   920.6 2269.48   924.4 2267.77   934.4 2266.85   935.6 2266.95   964.6  2270.2
  1014.8 2267.81  1075.1 2267.16  1538.1 2272.49  1659.3 2277.76  1810.7 2288.82
  1820.8 2290.81    1841 2298.85  1911.7 2337.34    1942 2352.26  2083.4 2409.98
#Mann= 3 , 0 , 0
       0     .06       0   920.6    .045       0   935.6     .06       0
Bank Sta=920.6,935.6
XS Rating Curve= 0 ,0
Exp/Cntr=0.3,0.1

Type RM Length L Ch R = 1 ,133448.4,862.1,855.1,848.2
XS GIS Cut Line= 3
     2250497.911      382002.405      2249765.41      382492.265
     2248355.346      383439.938
#Sta/Elev= 30
       0 2461.61   100.1 2445.83   150.2 2439.97   230.3 2437.24   310.4 2430.94
   350.5  2430.5   380.5 2427.88   420.6  2420.6   510.7 2399.83   540.7 2395.51
     721 2391.38   861.2 2377.06   881.2 2371.55   911.4 2355.69  1052.1 2271.29
  1072.2 2264.99  1112.4 2261.08  1113.9 2261.29  1128.9 2264.67  1152.6 2270.06
  1323.5 2267.66    1786 2274.02  1876.4 2279.28  2107.6 2304.06    2168 2319.75
  2238.3 2353.86    2359 2405.23  2389.1 2415.45  2449.4 2425.16  2580.1 2434.19
#Mann= 3 , 0 , 0
       0     .06       0  1113.9    .045       0  1128.9     .06       0
Bank Sta=1113.9,1128.9
XS Rating Curve= 0 ,0
Exp/Cntr=0.3,0.1

Type RM Length L Ch R = 1 ,132593.2,1035.3,1045,1054.7
XS GIS Cut Line= 3
     2250120.468      381503.363     2249302.581      381748.879
     2248135.915      383202.744
#Sta/Elev= 30
       0 2468.44    70.3  2463.9   130.6  2451.9   160.7 2448.94   200.9  2449.4
   281.3 2457.56   311.4 2457.92   361.7 2454.16     442 2440.82   532.5 2431.02
   602.8 2429.99   693.2  2434.1   723.3 2430.27   773.6 2415.66   813.8 2401.08
   853.9 2380.85   874.1 2366.72   934.6 2316.68     995  2275.5  1015.2 2259.43
  1025.2 2256.13  1031.9 2256.23  1046.9 2257.14  1337.6 2262.41  1680.2 2263.01
  1881.7 2270.33  2194.1 2299.77  2506.4 2337.76  2637.4 2375.95    2718 2395.68
#Mann= 3 , 0 , 0
       0     .06       0  1031.9    .045       0  1046.9     .06       0
Bank Sta=1031.9,1046.9
XS Rating Curve= 0 ,0
Exp/Cntr=0.3,0.1

Type RM Length L Ch R = 1 ,131547.3,1158.4,1159.5,1160.6
XS GIS Cut Line= 3
     2249347.492      380792.844     2247970.454      381766.838
     2247428.442      382664.052
#Sta/Elev= 30
       0 2401.41    80.3 2384.26   110.4 2381.22   170.7  2378.3     251 2381.93
   401.6  2406.6   461.8 2422.38     502 2438.26   522.1 2439.88   562.2 2428.58
   612.4 2404.71   823.3 2271.77   853.4 2256.73  1034.1 2255.18  1117.2 2249.81
  1124.5  2249.7  1132.2 2249.86  1174.6 2251.85  1536.1 2254.61  1636.5 2260.24
  1787.5 2274.69    1858 2277.86  1898.3 2282.49  2089.8 2320.85  2311.6 2394.77
  2351.9 2405.95  2472.8 2432.79  2664.4 2479.57  2704.7 2486.62  2734.9 2489.33
#Mann= 3 , 0 , 0
       0     .08       0  1117.2    .045       0  1132.2     .08       0
Bank Sta=1117.2,1132.2
XS Rating Curve= 0 ,0
Exp/Cntr=0.3,0.1

Type RM Length L Ch R = 1 ,130386.7,973.4,979.4,985.4
XS GIS Cut Line= 3
     2249160.422      380497.497      2248308.89      380561.591
     2246399.809      381472.639
#Sta/Elev= 30
       0 2421.59   411.9 2317.76   522.4 2302.92   733.4 2288.69   843.9 2272.57
  1307.2 2249.71  1569.1 2246.27  1636.4 2239.09  1639.6 2239.04  1651.4 2240.96
  1669.8 2245.82  1710.1 2249.96  1800.8 2248.82  1901.5 2256.55  2012.3 2297.77
  2042.6 2300.78  2062.7 2313.62  2153.4 2358.15    2385 2482.97  2405.2 2491.47
  2425.3 2492.78  2445.5 2488.74  2536.1 2459.36  2616.7 2452.02  2697.3 2465.19
    2788 2490.44  2848.4 2509.59  2918.9 2539.62    2929 2541.15  2969.3 2537.18
#Mann= 3 , 0 , 0
       0     .08       0  1636.4    .045       0  1651.4     .08       0
Bank Sta=1636.4,1651.4
XS Rating Curve= 0 ,0
Exp/Cntr=0.3,0.1

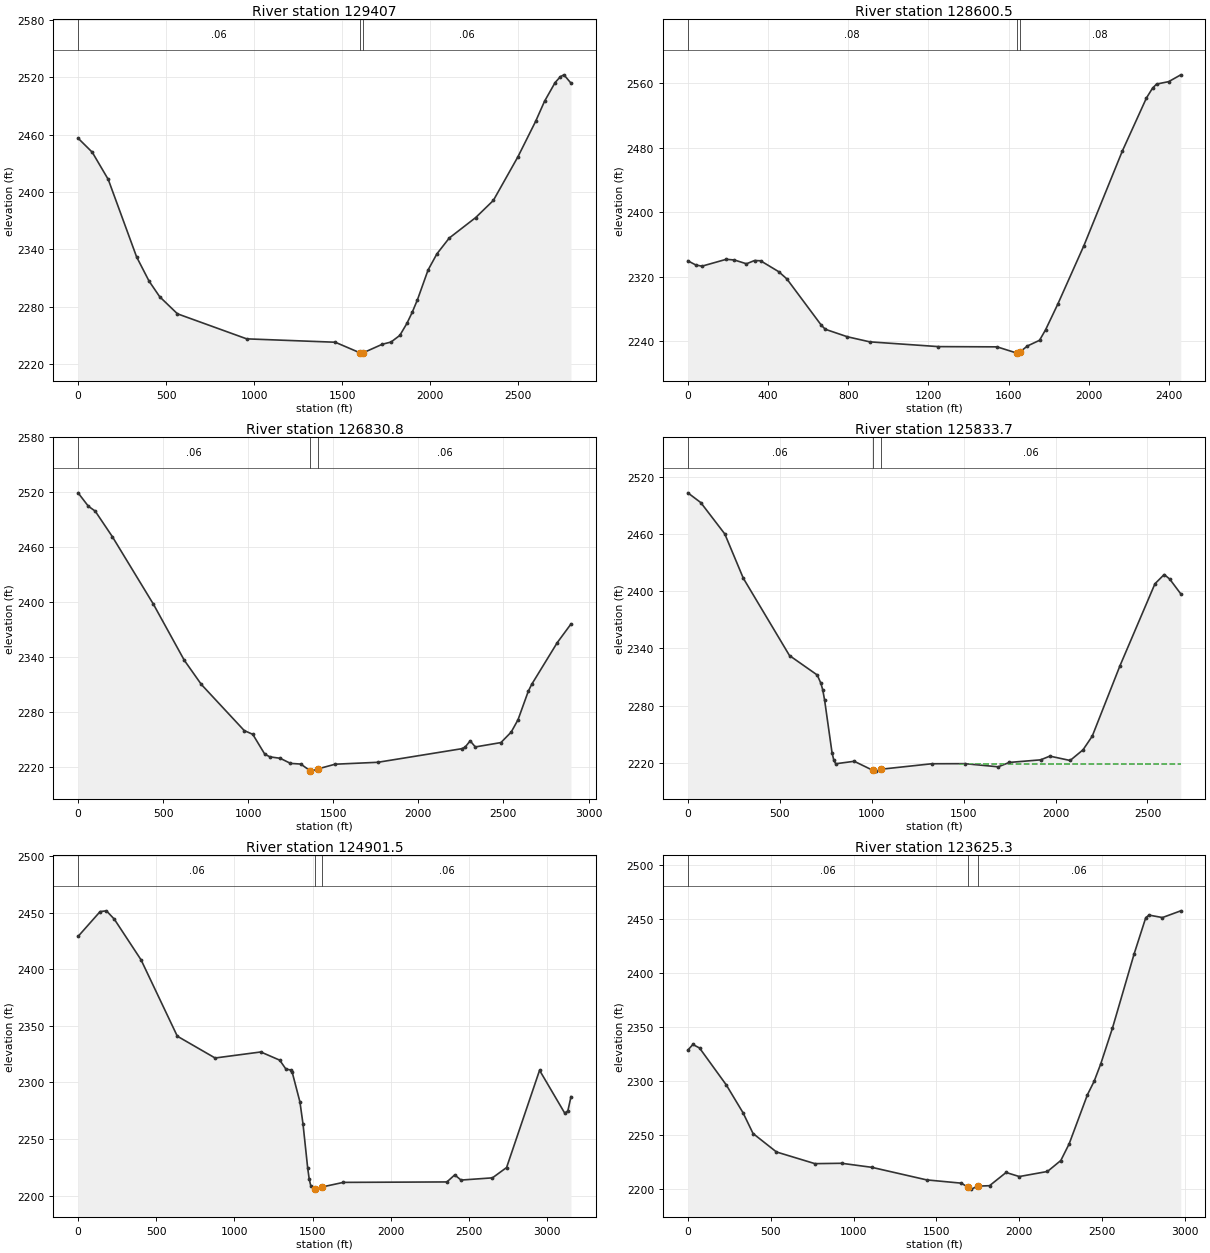
Type RM Length L Ch R = 1 ,129407  ,806.1,806.4,806.8
XS GIS Cut Line= 4
     2249017.857      379443.118     2247693.515      379901.282
     2247313.306       379968.99     2246308.098      380088.782
#Sta/Elev= 30
       0 2456.21    80.6 2441.53   171.4 2413.12   332.7 2332.07   403.3 2306.85
   463.8 2290.49   564.6 2272.67   957.8 2246.51  1460.8 2242.98  1603.8 2231.72
  1609.3 2231.59  1618.8 2231.88  1728.1 2240.86  1777.6 2243.17  1827.6 2250.12
  1867.7  2262.6  1897.8 2274.16  1927.9 2287.43    1988 2318.42  2038.1 2335.28
  2108.3 2351.85  2258.6 2373.26  2358.9 2391.16  2499.2 2437.02  2599.4 2473.94
  2649.5 2494.75  2709.7 2514.34  2739.7 2520.49  2759.8 2522.42  2799.9 2513.73
#Mann= 3 , 0 , 0
       0     .06       0  1603.8    .045       0  1618.8     .06       0
Bank Sta=1603.8,1618.8
XS Rating Curve= 0 ,0
Exp/Cntr=0.3,0.1

Type RM Length L Ch R = 1 ,128600.5,1777,1769.4,1761.9
XS GIS Cut Line= 3
     2248951.058      378891.924     2247099.507      379188.607
     2246582.178      379458.716
#Sta/Elev= 30
       0  2339.7    40.3 2334.44    70.6 2333.06   191.6 2341.57   231.9 2340.73
   292.4    2336   332.7 2340.06   362.9 2339.74   453.7 2326.13     494 2317.18
   665.4 2259.82   685.6 2254.65   796.4 2245.31   907.3 2239.04  1250.1 2233.11
  1542.5 2232.81  1639.8 2225.16  1643.3 2225.02  1654.8 2226.08  1693.7  2233.9
  1754.2 2240.93  1784.4    2254  1844.9 2285.64  1975.8 2358.67    2167 2475.87
  2287.7 2542.04  2317.9 2554.15    2338 2559.22  2398.4 2562.26  2458.8 2570.73
#Mann= 3 , 0 , 0
       0     .08       0  1639.8    .045       0  1654.8     .08       0
Bank Sta=1639.8,1654.8
XS Rating Curve= 0 ,0
Exp/Cntr=0.3,0.1

Type RM Length L Ch R = 1 ,126830.8,1000.6,997.1,993.7
XS GIS Cut Line= 4
     2248522.967      377210.988     2247417.473      377479.407
     2246986.663      377700.054     2245806.527      378183.804
#Sta/Elev= 30
       0 2519.45    60.4 2504.82   100.7 2499.47   201.4 2471.56     443 2397.65
   624.2 2336.44   724.8 2309.92   976.5 2259.58  1026.9 2255.42  1097.3 2233.77
  1127.6 2230.81    1188 2229.25  1248.5 2223.67    1309 2222.93  1364.1 2215.62
  1369.5 2215.21  1409.12217.609  1510.7 2222.77  1762.2 2224.88  2254.3  2239.7
  2274.4 2241.34  2304.6 2248.31  2334.7 2241.65  2485.3 2246.43  2545.6 2257.87
  2585.8  2271.4    2646 2302.49  2666.1 2310.05  2816.7 2355.78  2897.1 2376.07
#Mann= 3 , 0 , 0
       0     .06       0  1364.1    .045       0  1409.1     .06       0
Bank Sta=1364.1,1409.1
XS Rating Curve= 0 ,0
Exp/Cntr=0.3,0.1

Type RM Length L Ch R = 1 ,125833.7,943.2,932.2,921.2
XS GIS Cut Line= 3
     2247421.225      376241.644     2246353.518      377012.969
     2245262.293       377831.33
#Sta/Elev= 30
       0 2503.11    70.4 2492.88   201.1 2459.98   301.6 2413.61     553 2332.48
   703.8  2312.1   723.9 2303.32     734 2296.32     744 2285.65   784.3 2230.68
   794.3 2222.54   804.4 2219.03   904.9 2221.63  1005.82212.203  1025.6 2211.31
  1050.82213.294  1327.2 2219.04  1507.7 2219.13  1688.3 2215.83  1748.4 2220.42
  1918.9 2223.14  1969.1 2227.04  2079.4 2222.47  2149.6 2233.66  2199.8 2248.03
  2350.2 2321.66  2540.8 2407.76  2590.9 2417.44    2621  2412.7  2681.2 2397.18
#Mann= 3 , 0 , 0
       0     .06       0  1005.8    .045       0  1050.8     .06       0
#XS Ineff= 2 , 0
                          1476.1         2219.21
Permanent Ineff=
       F       F
Bank Sta=1005.8,1050.8
XS Rating Curve= 0 ,0
Exp/Cntr=0.3,0.1

Type RM Length L Ch R = 1 ,124901.5,1264.8,1276,1287.2
XS GIS Cut Line= 4
     2247320.146      375949.654     2246005.497      376067.566
     2245803.235      376476.758      2244641.46      377215.158
#Sta/Elev= 30
       0 2428.95   141.1 2450.92   181.4 2451.58   231.7 2444.26     403 2408.28
   634.8 2340.89   876.6 2321.62  1168.8 2326.95  1289.7 2319.72  1329.8  2311.8
  1359.6 2311.05  1369.5 2309.18  1419.2 2282.82    1439 2263.17  1468.8  2224.4
  1478.7 2214.62  1488.6  2208.7  1516.32206.133  1528.3 2205.83  1561.32207.742
    1697 2211.79  2359.2 2212.18  2409.4  2218.4  2449.6 2213.83  2650.6 2215.79
    2741  2224.9    2952 2310.76  3112.8 2272.97  3132.9 2274.91    3153 2287.49
#Mann= 3 , 0 , 0
       0     .06       0  1516.3    .045       0  1561.3     .06       0
Bank Sta=1516.3,1561.3
XS Rating Curve= 0 ,0
Exp/Cntr=0.3,0.1

Type RM Length L Ch R = 1 ,123625.3,1568.1,1581.2,1594.4
XS GIS Cut Line= 4
     2246106.052      374747.819     2245112.787      375525.303
     2244396.298      376033.922     2243564.817      375963.158
#Sta/Elev= 30
       0 2328.61    30.3 2333.82    70.6 2330.58   232.1 2296.31     333 2270.54
   393.6 2251.26   534.8 2234.17   766.9 2223.34   928.4 2223.68    1110 2219.94
  1441.1 2208.28  1650.8 2205.24  1690.7  2201.4  1710.7 2199.72  1749.32202.488
  1820.5  2202.9  1920.4 2215.14  2000.2 2211.39  2170.2  2216.1  2250.6 2226.26
  2300.9 2241.67  2411.5 2287.31  2451.7  2299.7  2491.9 2315.96  2562.3    2349
    2693  2417.8  2763.4 2451.47  2783.5 2453.77  2863.9 2451.52  2974.5 2457.75
#Mann= 3 , 0 , 0
       0     .06       0  1690.7    .045       0  1749.3     .06       0
Bank Sta=1690.7,1749.3
XS Rating Curve= 0 ,0
Exp/Cntr=0.3,0.1

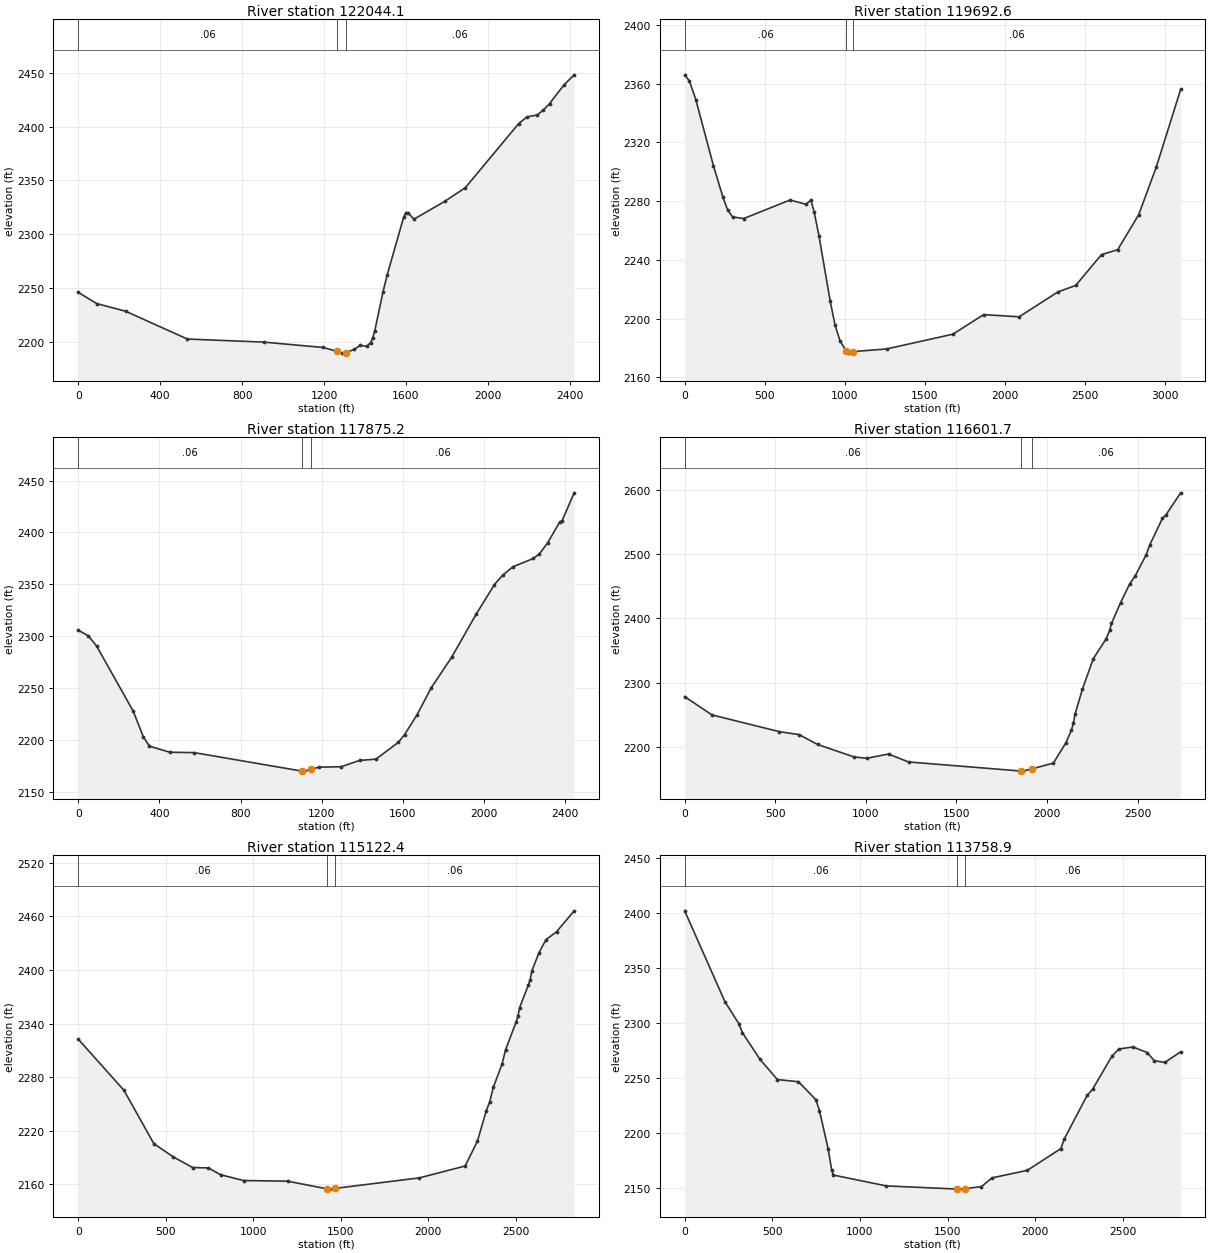
Type RM Length L Ch R = 1 ,122044.1,2369.8,2351.1,2332.1
XS GIS Cut Line= 3
     2245810.501      374278.039     2244172.338      374322.984
     2243724.037      374963.611
#Sta/Elev= 30
       0 2245.91    90.5  2235.4   231.2 2228.33   532.8 2202.45   904.8  2199.6
  1196.4 2194.58  1261.82191.046  1286.9 2189.34  1306.82189.879  1347.2 2192.79
  1377.4 2196.73  1407.5 2195.51  1427.6 2199.17  1437.7 2203.69  1447.8  2210.3
    1488 2246.54  1508.1 2262.08  1588.5 2315.78  1598.6 2319.86  1608.6 2320.12
  1638.8 2313.95  1789.2 2330.52  1889.4 2343.19    2150 2402.88  2190.1 2409.05
  2240.2  2410.9  2270.3  2415.4  2300.4  2421.4  2370.6 2438.74  2420.7 2448.22
#Mann= 3 , 0 , 0
       0     .06       0  1261.8    .045       0  1306.8     .06       0
Bank Sta=1261.8,1306.8
XS Rating Curve= 0 ,0
Exp/Cntr=0.3,0.1

Type RM Length L Ch R = 1 ,119692.6,1826,1817.4,1808.9
XS GIS Cut Line= 3
     2243913.127      371703.362     2243740.364      372441.782
       2242118.5      374129.772
#Sta/Elev= 30
       0 2365.98    29.9  2361.7    69.8 2349.02   179.6 2304.17   239.5 2282.49
   269.4 2273.78   299.4 2269.24   369.2 2268.17   658.6 2280.76   758.4 2277.87
   788.6 2280.74   808.8 2272.81   839.1 2256.45   909.7 2211.75     940 2195.62
   970.2 2185.04  1007.92178.115  1020.7 2176.55  1052.92177.598  1262.9 2179.41
  1676.6 2189.47  1868.3 2202.75  2090.2 2201.28  2332.4 2218.22  2443.4 2222.61
  2604.8 2243.61  2705.7 2246.93  2836.9 2270.68  2947.9 2303.46  3099.2    2356
#Mann= 3 , 0 , 0
       0     .06       0  1007.9    .045       0  1052.9     .06       0
Bank Sta=1007.9,1052.9
XS Rating Curve= 0 ,0
Exp/Cntr=0.3,0.1

Type RM Length L Ch R = 1 ,117875.2,1251.1,1273.5,1295.9
XS GIS Cut Line= 3
     2242590.047      371153.986      2242111.23      371667.643
     2241436.358      373273.661
#Sta/Elev= 30
       0 2305.72    50.2 2300.13    90.3 2290.48   270.9 2227.61     321 2202.72
   351.1 2193.78   451.4  2187.9   571.8 2187.55  1100.82169.781  1115.1 2169.69
  1145.82171.322  1185.6 2173.53  1296.3 2173.93    1387 2180.06  1467.5 2181.25
  1578.3 2197.52  1608.5 2204.91  1668.9 2223.67  1739.4  2249.9  1840.1 2279.45
  1960.9 2320.98  2051.6  2349.7  2091.8 2358.63  2142.2 2366.84  2242.9 2374.83
  2273.1 2379.33  2313.4 2389.83  2373.8 2410.29  2383.8 2410.77  2444.3 2438.19
#Mann= 3 , 0 , 0
       0     .06       0  1100.8    .045       0  1145.8     .06       0
Bank Sta=1100.8,1145.8
XS Rating Curve= 0 ,0
Exp/Cntr=0.3,0.1

Type RM Length L Ch R = 1 ,116601.7,1476.5,1479.2,1482
XS GIS Cut Line= 4
     2242441.433      370545.263      2241508.18      371370.591
     2240635.086      371541.575     2240154.481        371904.8
#Sta/Elev= 30
       0 2278.36   150.7 2250.04   522.4 2224.05     633 2219.39   733.4 2204.14
   934.4 2184.82  1004.7 2182.66  1125.3 2189.26  1235.8    2177  1855.6 2162.89
  1865.6 2162.73  1915.6 2166.11  2035.6 2175.22  2105.5 2207.19  2135.5 2226.67
  2145.6 2236.74  2155.6 2251.48  2195.8 2290.04    2256 2337.47  2326.3 2367.89
  2346.4 2381.54  2356.4 2392.14  2406.6 2424.51  2456.8 2453.54  2486.9 2465.92
  2547.2 2498.46  2567.3 2513.94  2637.5  2555.4  2657.6 2560.91    2738 2595.01
#Mann= 3 , 0 , 0
       0     .06       0  1855.6    .045       0  1915.6     .06       0
Bank Sta=1855.6,1915.6
XS Rating Curve= 0 ,0
Exp/Cntr=0.3,0.1

Type RM Length L Ch R = 1 ,115122.4,1377.3,1363.5,1349.8
XS GIS Cut Line= 3
     2242287.891      369981.985     2240451.031      370091.198
     2239458.605       370165.11
#Sta/Elev= 30
       0 2322.56   261.4 2265.32   432.4 2205.55     543 2190.81   653.6 2178.87
   744.1 2178.43   814.5 2170.78   945.2  2164.3  1196.6 2163.59  1423.52154.972
  1437.9 2154.68  1468.52155.523  1950.7 2167.28    2212 2180.57  2282.4 2208.43
  2332.7 2242.46  2352.8 2252.53  2372.9 2268.48  2423.1 2294.62  2443.2  2310.7
  2503.6 2341.77  2513.6 2347.99  2523.7 2357.94  2573.9 2383.36    2584 2389.21
    2594 2399.18  2634.2 2419.32  2674.4 2433.99  2734.8 2442.83  2835.3  2466.2
#Mann= 3 , 0 , 0
       0     .06       0  1423.5    .045       0  1468.5     .06       0
Bank Sta=1423.5,1468.5
XS Rating Curve= 0 ,0
Exp/Cntr=0.3,0.1

Type RM Length L Ch R = 1 ,113758.9,1484,1478.9,1473.8
XS GIS Cut Line= 3
      2241628.64      367912.669      2240968.65      368413.487
     2239394.512      369647.781
#Sta/Elev= 30
       0 2401.56   229.6 2318.99   309.4 2298.89   329.4 2290.75   429.2 2266.67
     529 2248.17   648.8 2246.27   748.6 2229.83   768.6 2220.02   818.5 2185.18
   838.6 2165.81   848.6  2161.4  1150.2 2151.56  1552.82148.705  1562.3 2148.63
  1597.82148.981    1693 2150.98  1753.3 2158.87  1954.3  2165.7  2145.3  2185.4
  2165.4  2194.3  2296.1 2233.98  2326.2 2239.24  2436.8 2269.42    2477 2276.02
  2557.4 2277.84  2637.9  2272.8  2678.1 2265.45  2738.4 2263.75  2828.8 2273.38
#Mann= 3 , 0 , 0
       0     .06       0  1552.8    .045       0  1597.8     .06       0
Bank Sta=1552.8,1597.8
XS Rating Curve= 0 ,0
Exp/Cntr=0.3,0.1

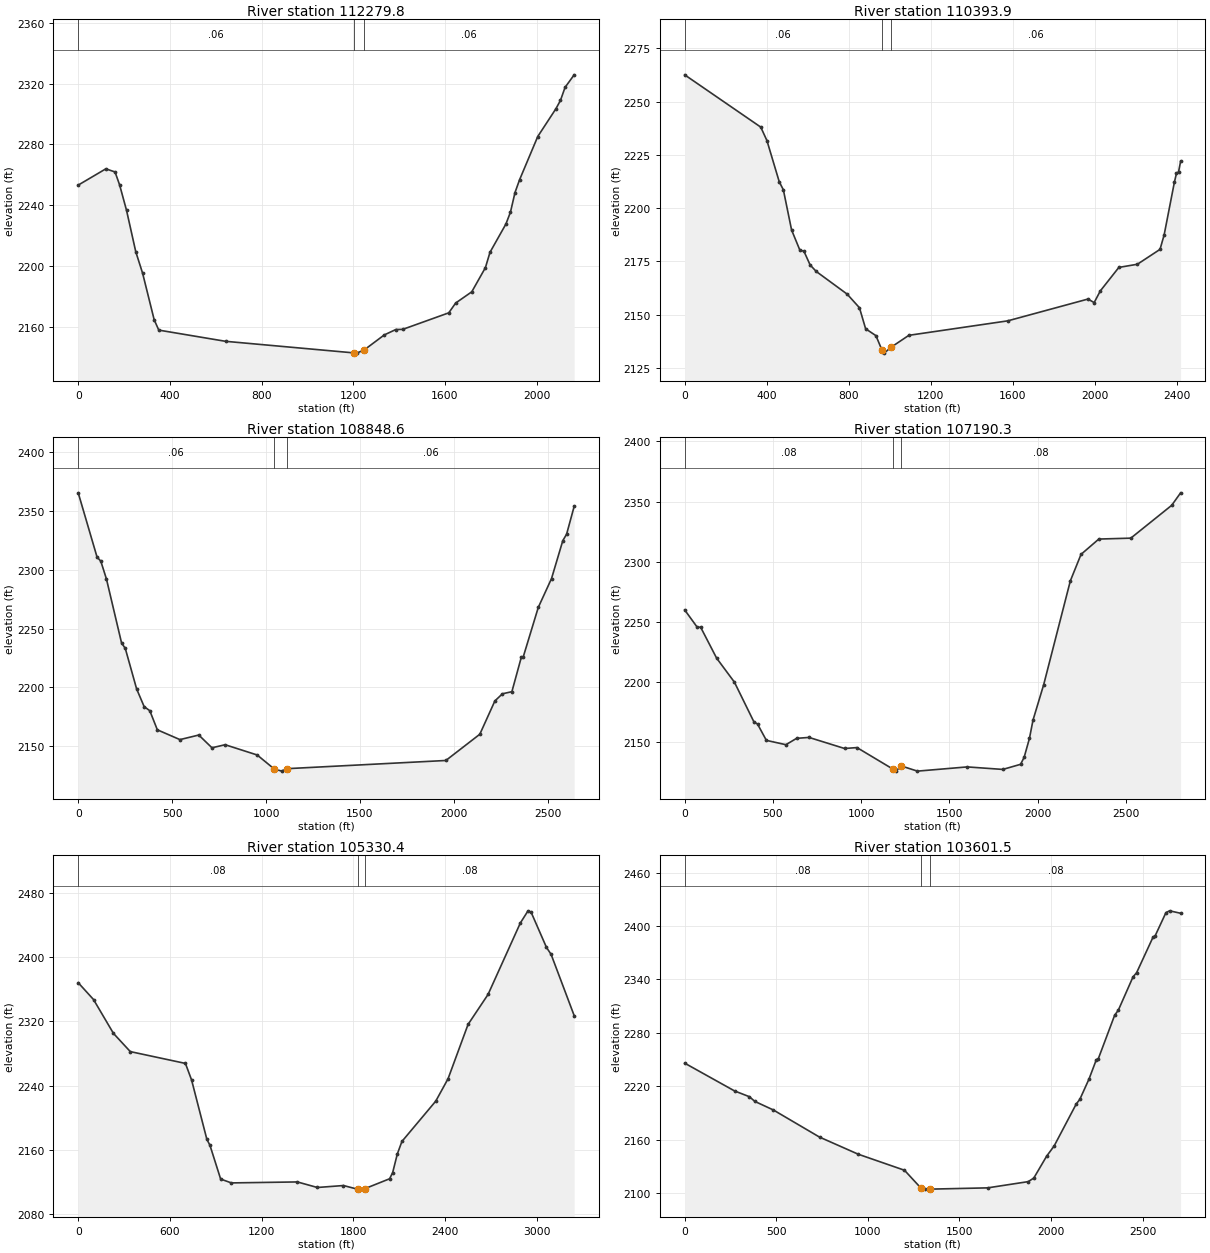
Type RM Length L Ch R = 1 ,112279.8,1889.5,1885.7,1881.2
XS GIS Cut Line= 3
     2240112.412      367140.198     2238988.234      368438.309
     2238655.541      368736.349
#Sta/Elev= 30
       0 2253.21   120.5 2263.94   160.7 2261.88   180.8 2253.26   210.9 2236.53
   251.1 2209.32   281.2 2195.02   331.4 2164.49   351.5 2157.65   642.7 2150.27
  1203.12142.626  1215.1 2142.48  1248.12144.611  1335.6 2154.49  1385.8 2158.03
    1416 2158.14  1616.8 2169.03  1646.9 2175.49  1717.2 2182.89  1776.8 2198.85
  1796.6  2208.9  1866.1 2227.55    1886 2235.39  1905.8 2248.31  1925.7 2256.71
  2005.1 2285.24  2084.5 2303.58  2104.3 2309.08  2124.2 2317.61  2163.9 2325.89
#Mann= 3 , 0 , 0
       0     .06       0  1203.1    .045       0  1248.1     .06       0
Bank Sta=1203.1,1248.1
XS Rating Curve= 0 ,0
Exp/Cntr=0.3,0.1

Type RM Length L Ch R = 1 ,110393.9,1548.6,1545.5,1542.4
XS GIS Cut Line= 3
     2238602.495      365838.776     2238382.744      366589.589
     2237499.165      367967.607
#Sta/Elev= 30
       0  2262.6   371.1 2238.05   401.2 2231.73   461.4 2212.36   481.4 2208.61
   521.5 2189.75   561.7 2180.33   581.7 2179.78   611.8 2173.35   641.9 2170.26
   792.4 2159.64   852.6 2153.23   882.7 2143.36     933 2140.12   961.82133.485
   973.1 2131.92  1006.82134.681  1093.6 2140.28  1575.7 2147.07  1967.4 2157.31
  1997.5 2155.65  2027.6 2161.14    2118 2172.17  2208.4 2173.65  2318.8 2180.64
  2338.9 2187.42  2389.2 2212.31  2399.2 2216.36  2409.2 2217.03  2419.3 2221.96
#Mann= 3 , 0 , 0
       0     .06       0   961.8    .045       0  1006.8     .06       0
Bank Sta=961.8,1006.8
XS Rating Curve= 0 ,0
Exp/Cntr=0.3,0.1

Type RM Length L Ch R = 1 ,108848.6,1638.5,1658,1677.5
XS GIS Cut Line= 3
     2237523.311      365206.978      2237021.64      365896.074
     2236269.789      367517.992
#Sta/Elev= 30
       0 2365.58   100.3 2310.87   120.3 2307.39   150.4 2292.17   230.6 2237.87
   250.7 2233.07   310.9 2198.69     351 2183.58   381.1  2180.1   421.2 2163.85
   541.5 2155.51   641.8  2159.4     712 2148.55   782.2 2151.15   952.8 2142.42
  1043.2 2130.53  1083.4 2128.68  1110.52130.761  1957.1 2137.74  2137.9 2160.08
  2218.2 2188.45  2258.4 2194.52  2308.6  2196.3  2358.9 2225.66  2368.9 2225.82
  2449.2 2268.06  2519.6 2292.59  2579.8 2324.91  2599.9 2330.36  2640.1 2353.99
#Mann= 3 , 0 , 0
       0     .06       0  1043.2    .045       0  1110.5     .06       0
Bank Sta=1043.2,1110.5
XS Rating Curve= 0 ,0
Exp/Cntr=0.3,0.1

Type RM Length L Ch R = 1 ,107190.3,1863.1,1859.3,1855.5
XS GIS Cut Line= 3
     2236601.851       364726.29     2235873.831      365420.756
     2234285.317      366273.698
#Sta/Elev= 30
       0 2259.85    70.4 2245.57    90.6 2245.39   181.1 2219.67   281.7 2199.74
   392.4 2166.61   412.5  2164.9   462.8 2151.28   573.5 2147.68   633.9 2152.97
   704.3 2153.74   905.5 2144.53     976 2145.28  1177.4 2127.57  1197.5 2125.86
  1226.3 2130.02  1318.4 2125.69  1600.4  2129.2  1801.9 2127.11  1902.6 2131.35
  1922.8 2137.14    1953 2152.98  1973.1 2168.15  2033.6 2197.64  2184.6 2284.03
  2245.1 2306.05  2345.8  2318.8  2527.1 2319.56  2758.8 2346.89  2809.2 2357.27
#Mann= 3 , 0 , 0
       0     .08       0  1177.4    .045       0  1226.3     .08       0
Bank Sta=1177.4,1226.3
XS Rating Curve= 0 ,0
Exp/Cntr=0.3,0.1

Type RM Length L Ch R = 1 ,105330.4,1735,1728.9,1722.4
XS GIS Cut Line= 3
     2236180.663      362899.615     2235291.494      363781.725
     2233533.611      364718.586
#Sta/Elev= 30
       0 2368.22   100.2 2347.22   230.5 2305.03   340.7 2282.31   701.4 2267.58
   741.5 2247.01   841.7 2172.87   861.7 2165.55   931.8 2123.38    1002 2118.57
  1433.6 2119.79  1564.4 2112.87  1735.4  2115.3  1825.9 2110.82  1828.82110.843
  1873.82111.291  2037.2 2123.74  2057.3 2131.55  2087.5  2154.6  2117.7 2170.27
    2339 2220.55  2419.5 2248.46  2550.3 2316.19  2681.1 2353.57  2892.3 2442.65
  2942.6 2457.85  2962.8 2456.13  3063.4  2412.2  3093.5 2403.59  3244.4 2327.28
#Mann= 3 , 0 , 0
       0     .08       0  1828.8    .045       0  1873.8     .08       0
Bank Sta=1828.8,1873.8
XS Rating Curve= 0 ,0
Exp/Cntr=0.3,0.1

Type RM Length L Ch R = 1 ,103601.5,1398.9,1396,1393.5
XS GIS Cut Line= 3
     2234919.875      361937.347     2233461.656      363431.446
     2233319.331      364034.992
#Sta/Elev= 30
       0 2245.88   272.3 2214.64     353 2208.17   383.3 2202.84   484.1 2193.24
   736.3 2162.72   948.1 2143.44  1200.2 2125.44    1291 2105.18  1311.2 2104.22
  1341.4 2104.22  1654.1 2105.64    1876 2112.66  1906.2 2116.66  1976.8 2141.44
  2017.2  2152.7  2137.8 2199.88  2157.8 2205.25  2207.8 2228.07  2247.8  2249.8
  2257.8 2250.46  2347.8 2299.79  2367.8 2305.45  2447.8 2342.76  2467.8 2347.66
  2557.8  2387.8  2567.8  2388.6  2627.8 2415.15  2647.8 2417.16  2707.9 2414.42
#Mann= 3 , 0 , 0
       0     .08       0    1291    .045       0  1341.4     .08       0
Bank Sta=1291,1341.4
XS Rating Curve= 0 ,0
Exp/Cntr=0.3,0.1