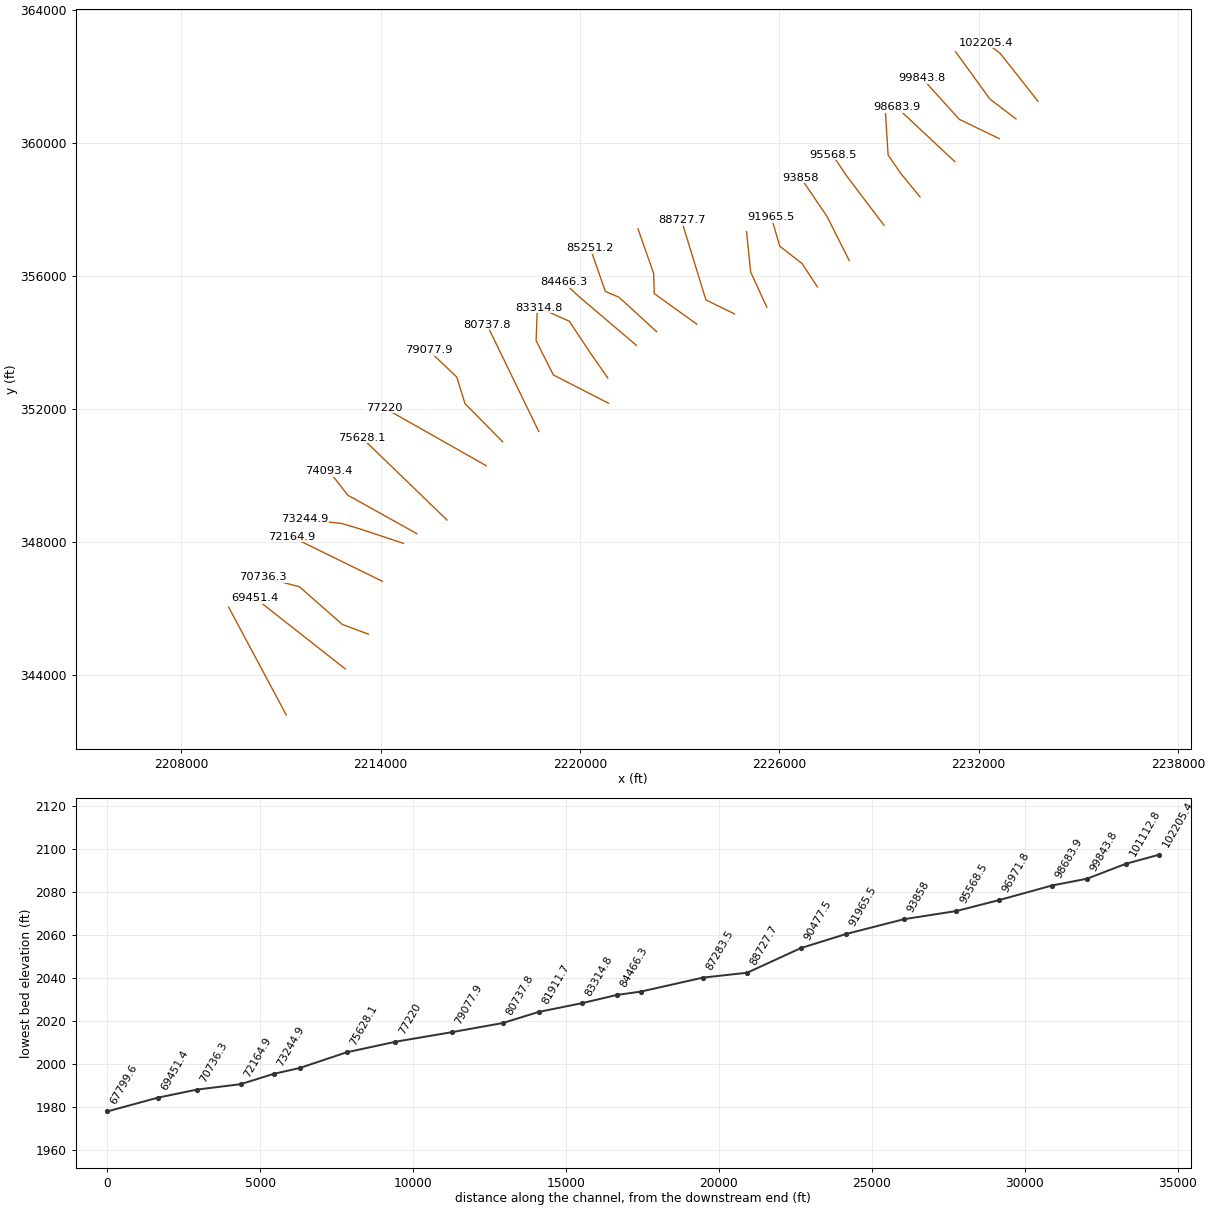
HEC-RAS study AntCk.prj: AntCk

--- AntCk.g01 (geometry) --- (continued)

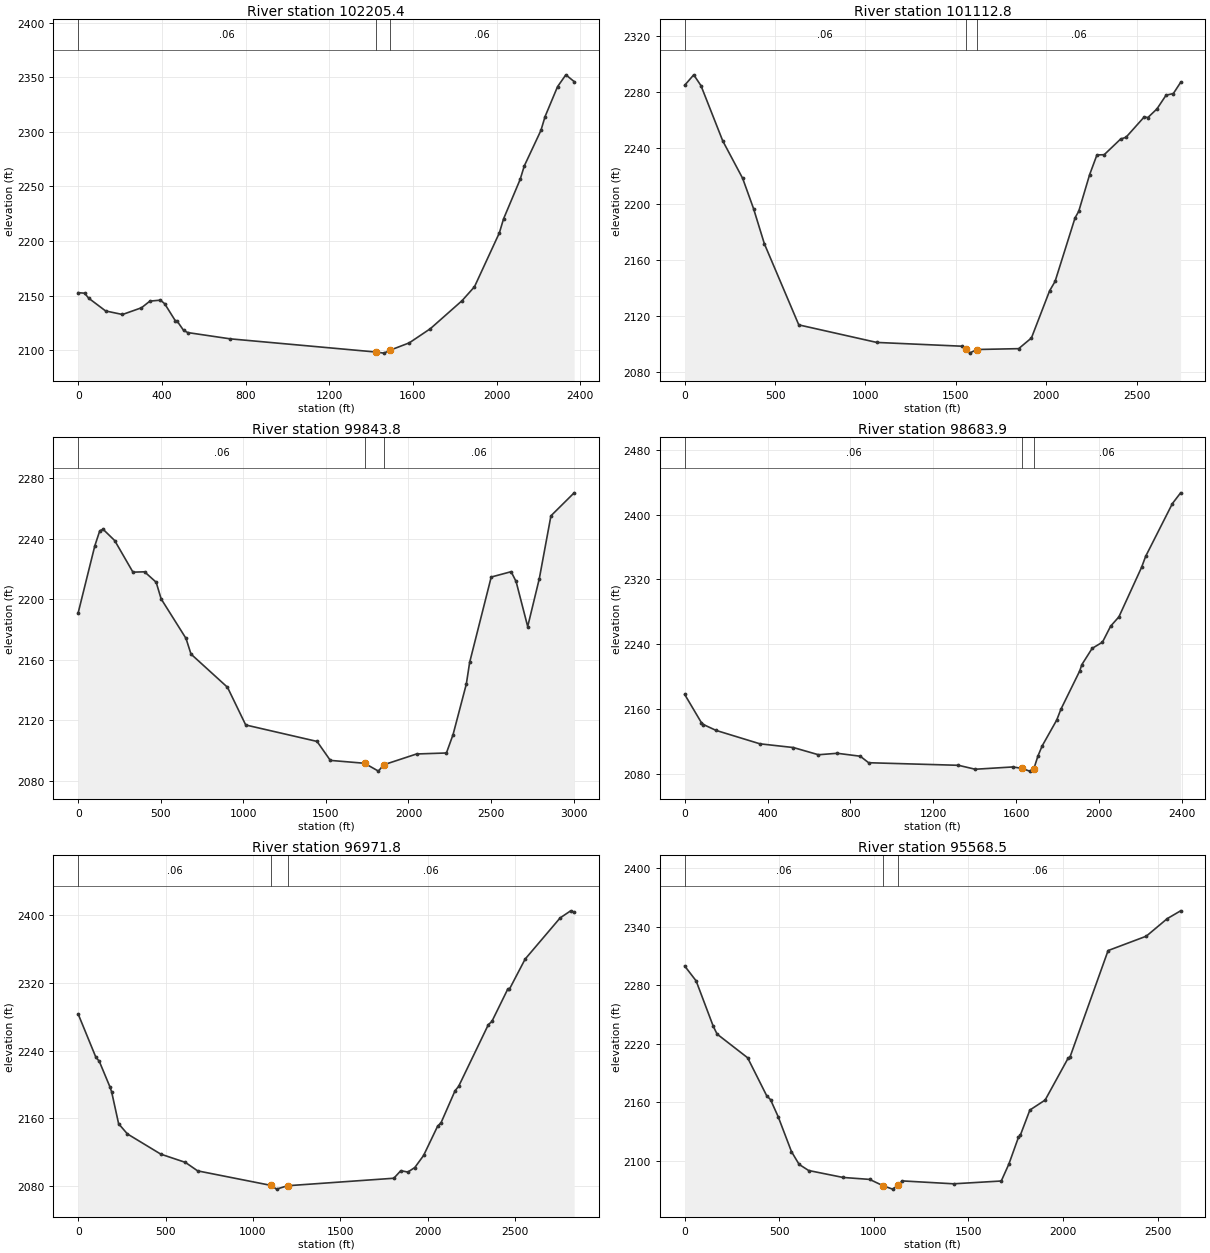
Type RM Length L Ch R = 1 ,102205.4,1093.1,1092.4,1091.5
XS GIS Cut Line= 3
     2233781.783      361246.485      2232643.48      362685.704
     2232216.002       363009.49
#Sta/Elev= 30
       0 2152.76    30.2 2152.29    50.4 2147.66   131.1 2136.02   211.7 2132.78
   302.5 2138.93   342.8 2145.04   393.2 2145.91   413.4 2142.64   463.8 2127.22
   473.9 2126.47   504.1 2118.16   524.3 2116.21   725.9  2110.5  1421.6 2098.43
  1461.9  2097.4  1492.2 2100.15  1582.9 2106.81  1683.7 2119.78    1835  2145.4
  1894.6 2158.16  2013.7 2207.56  2033.6 2220.33    2113 2256.48  2132.9 2268.89
  2212.3 2301.33  2232.2 2314.08  2291.8 2341.42  2331.5 2352.26  2371.2 2346.08
#Mann= 3 , 0 , 0
       0     .06       0  1421.6    .045       0  1492.2     .06       0
Bank Sta=1421.6,1492.2
XS Rating Curve= 0 ,0
Exp/Cntr=0.3,0.1

Type RM Length L Ch R = 1 ,101112.8,1266.4,1269.1,1271.8
XS GIS Cut Line= 3
     2233120.081       360714.42     2232337.811      361307.569
     2231302.984      362732.683
#Sta/Elev= 30
       0 2284.81    50.1 2292.28    90.2 2284.52   210.4 2245.05   320.6 2218.22
   380.7 2196.62   440.8 2171.38   631.1 2113.36  1062.2 2100.81  1535.2 2098.09
  1555.4 2095.91  1575.5 2093.15  1615.8 2095.74  1847.2 2096.35  1917.7 2103.98
  2018.3 2137.74  2048.5 2144.45  2159.2 2190.01  2179.3 2194.58  2239.7 2220.88
    2280 2234.96  2320.2 2235.12  2410.8  2246.3    2441 2247.61  2541.6 2262.16
  2561.8 2261.72  2612.1 2267.91  2662.4 2277.71  2702.7 2278.89  2742.9 2286.88
#Mann= 3 , 0 , 0
       0     .06       0  1555.4    .045       0  1615.8     .06       0
Bank Sta=1555.4,1615.8
XS Rating Curve= 0 ,0
Exp/Cntr=0.3,0.1

Type RM Length L Ch R = 1 ,99843.8 ,1158.1,1159.7,1161.4
XS GIS Cut Line= 3
     2232617.634      360120.382     2231414.446      360700.689
     2230296.521        361937.9
#Sta/Elev= 30
       0 2190.99   100.4 2235.14   130.6 2245.18   150.7 2246.14     221 2238.68
   331.4  2217.8   401.8 2218.02   472.1 2211.12   502.2 2200.12   652.8 2173.97
     683 2163.62   903.9 2141.67  1014.4 2116.74  1446.3 2105.86  1526.7 2093.32
  1734.22091.412    1818 2086.22  1849.22090.378    2049 2097.56  2229.8 2098.22
    2270 2110.38  2350.4 2143.82  2370.4 2158.12    2501 2214.56  2621.6  2218.1
  2651.7 2211.62    2722 2181.82  2792.3 2213.51  2862.7 2255.04  3003.3 2270.25
#Mann= 3 , 0 , 0
       0     .06       0  1734.2    .045       0  1849.2     .06       0
Bank Sta=1734.2,1849.2
XS Rating Curve= 0 ,0
Exp/Cntr=0.3,0.1

Type RM Length L Ch R = 1 ,98683.9 ,1715.1,1711,1706.7
XS GIS Cut Line= 3
     2231278.358      359430.839     2229863.072      360753.247
     2229531.364      361067.264
#Sta/Elev= 30
       0 2177.88    80.7 2142.94    90.8 2140.58   151.3 2133.39   363.2 2116.78
   524.6 2112.18   645.6 2103.27   736.4 2105.07   847.4 2101.44   887.8  2093.4
  1321.6 2090.21  1402.3 2085.34  1583.9 2088.18  1628.4 2086.42  1664.6 2083.01
  1684.8 2085.56  1704.9  2101.6  1725.1 2114.03  1795.7 2146.19  1815.9 2159.55
  1906.7 2206.89  1916.8 2214.64  1966.7 2234.82  2016.4 2242.45  2056.1 2262.36
  2095.8 2273.76  2205.1 2334.91  2224.9 2348.58    2354 2413.87  2393.7 2427.15
#Mann= 3 , 0 , 0
       0     .06       0  1628.4    .045       0  1684.8     .06       0
Bank Sta=1628.4,1684.8
XS Rating Curve= 0 ,0
Exp/Cntr=0.3,0.1

Type RM Length L Ch R = 1 ,96971.8 ,1401.3,1403.2,1404.4
XS GIS Cut Line= 4
     2230233.671      358367.265     2229665.982      359058.563
     2229272.263      359626.251     2229194.435      360876.081
#Sta/Elev= 30
       0 2283.17   100.5 2232.46   120.6 2227.38   180.9 2197.46     191 2191.51
   231.2 2153.59   281.4 2141.55   472.4 2117.66   613.1 2107.91   683.4 2097.87
  1104.8 2080.63  1134.8 2076.29  1197.72080.298  1805.8 2089.16  1845.8 2098.09
  1885.9 2096.46    1926 2101.85  1976.1 2116.07  2056.2 2150.63  2076.3 2154.92
  2156.4 2192.72  2176.4 2197.71  2346.7 2270.77  2366.8  2274.5  2456.9 2312.41
    2467 2312.61  2557.1 2348.24  2757.5 2396.94  2817.6  2405.3  2837.6 2403.84
#Mann= 3 , 0 , 0
       0     .06       0  1104.8    .045       0  1197.7     .06       0
Bank Sta=1104.8,1197.7
XS Rating Curve= 0 ,0
Exp/Cntr=0.3,0.1

Type RM Length L Ch R = 1 ,95568.5 ,1712.3,1710.2,1708.7
XS GIS Cut Line= 3
     2229148.653      357515.733     2228004.121      359026.516
     2227601.245      359630.829
#Sta/Elev= 30
       0 2299.97    60.5 2284.71   151.2 2238.09   171.4 2230.13   332.7 2205.88
   433.5 2166.96   453.7 2162.96     494 2145.55   564.6 2109.64   604.9 2096.55
   655.3 2090.27   836.8 2083.16   977.9 2081.15  1047.22074.818  1098.9 2071.18
  1129.2 2075.16  1149.3 2079.62  1421.5 2076.64  1673.6 2079.51  1713.9 2096.92
  1764.3 2124.24  1774.4 2126.45  1824.8 2152.27  1905.5 2162.51  2026.5 2205.27
  2036.6 2206.43  2238.3 2315.78  2440.1 2330.51    2551 2348.52  2621.7 2356.52
#Mann= 3 , 0 , 0
       0     .06       0  1047.2    .045       0  1129.2     .06       0
Bank Sta=1047.2,1129.2
XS Rating Curve= 0 ,0
Exp/Cntr=0.3,0.1

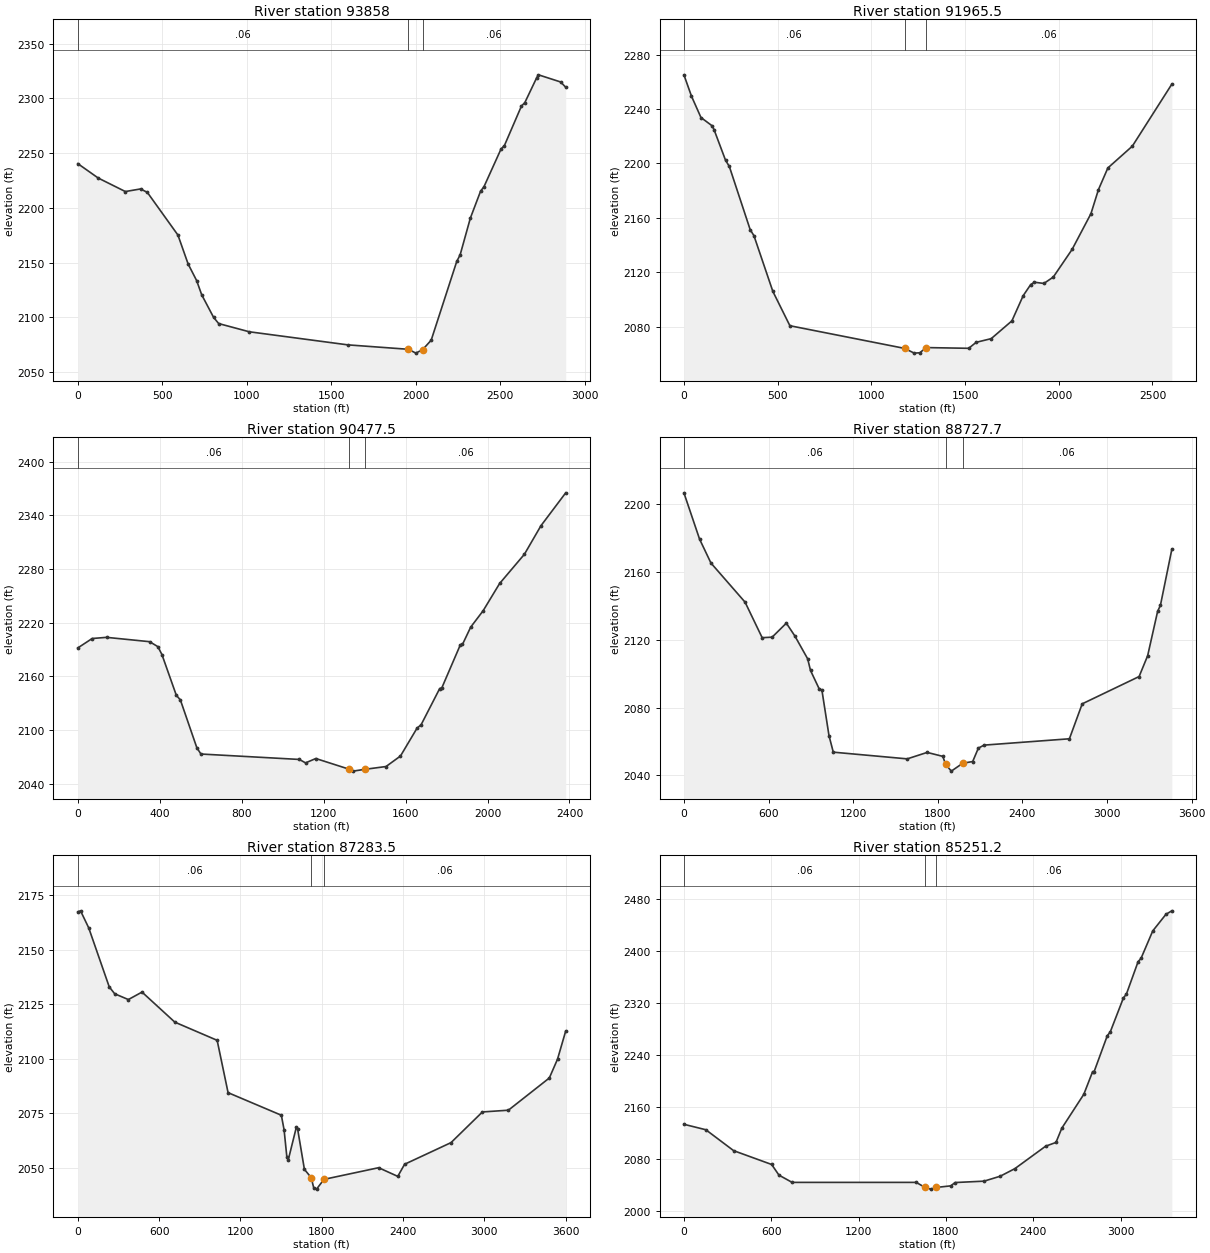
Type RM Length L Ch R = 1 ,93858   ,1885,1892.3,1899.6
XS GIS Cut Line= 3
     2228100.261      356458.184     2227436.432      357776.686
     2226644.416       358944.11
#Sta/Elev= 30
       0 2240.37   120.5 2227.25   281.2 2214.89   371.6 2217.28   411.7 2214.06
   592.5 2175.14   652.7 2148.76   702.9 2133.67   733.1 2120.62   803.4 2100.04
   833.5 2094.38  1014.2 2086.89  1597.1 2074.94  1956.42070.887  2000.2 2067.39
  2040.5 2070.62  2090.9 2079.19    2242 2151.04  2262.2 2157.11  2322.6 2190.61
  2383.1 2215.21  2403.2 2219.29    2504 2253.68  2524.2 2256.89  2624.9 2292.92
  2645.1 2296.11  2715.6 2318.93  2725.7 2321.44  2856.7 2314.92  2886.9 2310.11
#Mann= 3 , 0 , 0
       0     .06       0  1956.4    .045       0  2040.5     .06       0
Bank Sta=1956.4,2040.5
XS Rating Curve= 0 ,0
Exp/Cntr=0.3,0.1

Type RM Length L Ch R = 1 ,91965.5 ,1506.7,1487.9,1469.1
XS GIS Cut Line= 4
     2227143.067      355662.638     2226684.422      356363.948
     2226011.223      356885.657     2225756.258      357762.952
#Sta/Elev= 30
       0 2265.21    40.4  2249.5    90.9 2233.82   151.4 2227.62   161.5 2224.62
   222.1 2202.36   242.3  2197.8   353.4 2151.39   373.6 2146.89   474.5 2105.92
   565.4 2080.67  1177.22064.009  1228.7 2060.52  1258.8 2060.78  1292.22064.603
  1519.3 2064.07  1559.4 2068.47  1639.6 2071.18  1749.9 2084.24  1810.1 2102.77
  1850.3 2110.96  1870.4 2112.66  1920.6 2111.77  1970.8 2116.48  2071.2 2136.82
  2171.6 2163.07  2211.7 2180.77  2261.9 2196.71  2392.4 2212.73  2603.2 2258.35
#Mann= 3 , 0 , 0
       0     .06       0  1177.2    .045       0  1292.2     .06       0
Bank Sta=1177.2,1292.2
XS Rating Curve= 0 ,0
Exp/Cntr=0.3,0.1

Type RM Length L Ch R = 1 ,90477.5 ,1777.6,1751,1734.9
XS GIS Cut Line= 3
     2225621.461      355054.145     2225136.223      356109.615
     2225011.223      357323.157
#Sta/Elev= 30
       0 2191.78    70.1  2202.3   140.2  2203.6   350.5 2198.75   390.6 2193.22
   410.6 2184.36   480.7 2138.85   500.7 2133.56   580.8 2080.23   600.9 2073.06
  1081.6 2066.99  1111.6 2063.13  1161.7 2068.03    1323 2056.19  1343.2 2053.92
  1403.6 2056.01  1504.5 2059.07    1575 2070.82  1655.7 2101.95  1675.9  2105.9
  1766.6 2146.37  1776.7 2147.01  1867.4 2195.33  1877.5 2195.62  1917.8 2215.06
  1978.3 2233.32    2059 2263.86    2180 2296.59  2260.6 2328.47  2381.6 2365.31
#Mann= 3 , 0 , 0
       0     .06       0    1323    .045       0  1403.6     .06       0
Bank Sta=1323,1403.6
XS Rating Curve= 0 ,0
Exp/Cntr=0.3,0.1

Type RM Length L Ch R = 1 ,88727.7 ,1418.8,1442.7,1456.1
XS GIS Cut Line= 3
     2224649.684      354851.109     2223788.503      355271.067
     2223054.574      357662.233
#Sta/Elev= 30
       0 2206.84   110.9 2179.51   191.6 2165.38   433.7 2142.26   554.7  2121.3
   625.3 2121.58   726.2 2129.88   786.7 2122.28   877.4 2108.81   897.6 2101.92
   958.1 2091.24   978.3 2090.35  1028.7  2063.4    1059 2053.68  1583.4 2049.72
  1724.6 2053.53  1835.6  2051.2  1855.8  2046.4  1896.1 2042.48  1976.8 2047.13
  2047.4 2048.15  2087.7 2056.07  2128.1 2057.84  2733.2 2061.58    2824 2082.22
  3227.4 2098.34  3287.9 2110.62  3358.5 2136.78  3378.7 2140.47  3459.4 2173.45
#Mann= 3 , 0 , 0
       0     .06       0  1855.8    .045       0  1976.8     .06       0
Bank Sta=1855.8,1976.8
XS Rating Curve= 0 ,0
Exp/Cntr=0.3,0.1

Type RM Length L Ch R = 1 ,87283.5 ,2005.7,2032.2,2058.7
XS GIS Cut Line= 4
     2223512.974      354544.525     2222234.939      355460.676
     2222216.098       356067.43     2221745.688      357407.912
#Sta/Elev= 30
       0 2167.49    20.2 2167.94    80.6  2160.1   231.8 2133.05   272.2 2129.87
     373 2127.22   473.8 2130.65   715.7 2116.86  1028.2 2108.51  1108.8 2084.49
  1501.9 2074.13  1522.1 2067.45  1542.2 2055.15  1552.3  2053.5  1612.3 2068.57
  1622.2 2067.75    1672 2049.31  1721.8 2045.52  1741.7 2040.63  1761.6 2040.22
  1816.62044.702  2219.8 2050.05  2360.9 2046.07  2411.3 2051.63  2753.8 2061.56
  2985.6 2075.64    3177 2076.44  3479.2 2091.22  3539.7 2099.86  3600.2  2112.8
#Mann= 3 , 0 , 0
       0     .06       0  1721.8    .045       0  1816.6     .06       0
Bank Sta=1721.8,1816.6
XS Rating Curve= 0 ,0
Exp/Cntr=0.3,0.1

Type RM Length L Ch R = 1 ,85251.2 ,791.2,784.8,778.5
XS GIS Cut Line= 4
     2222306.903      354316.615     2221171.947      355352.448
     2220762.733      355526.461     2220310.802       356819.95
#Sta/Elev= 30
       0 2133.33   150.6 2124.93   341.5 2092.81   602.6 2071.58   652.8 2055.22
   743.2 2044.08  1595.9 2044.08  1655.2 2036.42  1694.7 2033.72  1734.2 2036.34
    1833 2038.76  1862.7 2043.84  2061.8 2045.98  2172.7 2053.56  2273.4 2065.21
    2485 2099.74  2555.5 2105.42  2595.8 2127.38  2746.9 2179.43  2807.4 2214.23
  2817.5 2214.09  2908.1 2269.42  2928.3 2275.09    3019 2327.54  3039.1 2333.17
  3119.7 2383.14  3139.8 2388.21  3220.4 2430.41  3311.1 2455.94  3351.4 2461.26
#Mann= 3 , 0 , 0
       0     .06       0  1655.2    .045       0  1734.2     .06       0
Bank Sta=1655.2,1734.2
XS Rating Curve= 0 ,0
Exp/Cntr=0.3,0.1

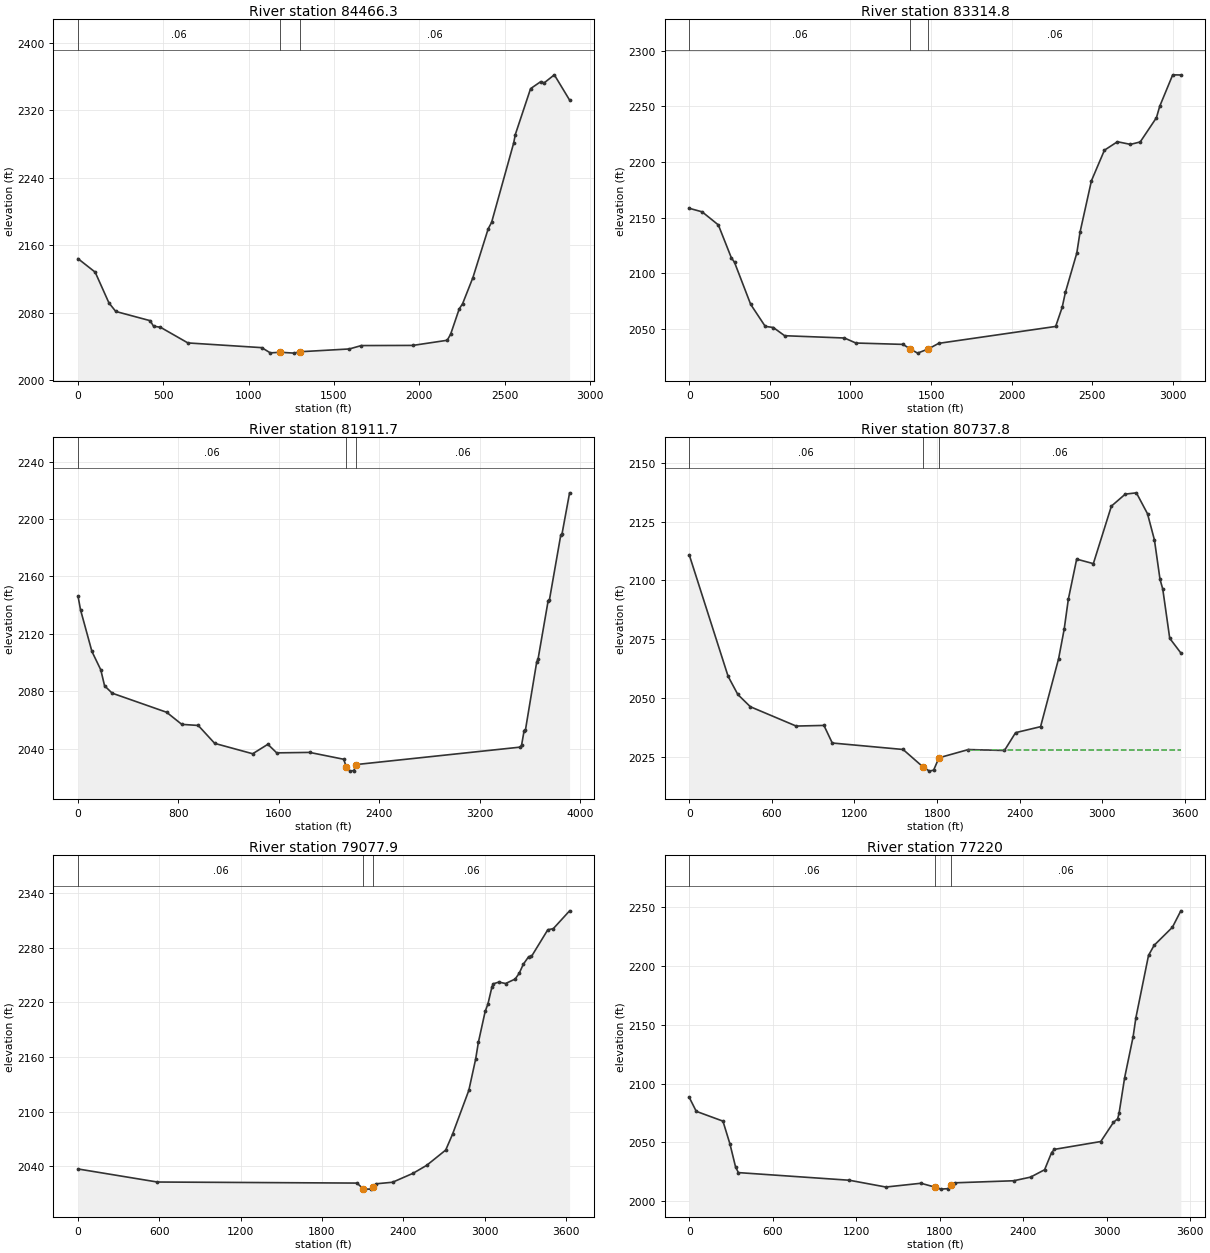
Type RM Length L Ch R = 1 ,84466.3 ,1157.4,1151.4,1144.7
XS GIS Cut Line= 3
     2221694.103       353908.49     2219937.269      355399.442
     2219519.089      355796.142
#Sta/Elev= 30
       0 2144.23   100.6 2128.23   181.1 2091.82   221.4 2081.58   422.6 2070.65
   442.7  2064.1     483 2062.86     644 2044.25  1076.6 2038.65    1127 2032.45
  1184.32033.154  1267.8 2032.15  1299.3 2033.76  1589.8  2037.1  1660.2 2041.12
  1962.1  2041.3  2163.4  2047.4  2183.5 2054.56  2233.8 2084.58  2253.9  2090.9
  2314.2 2121.85  2403.6 2179.66  2423.5 2187.23  2552.7 2281.22  2562.6 2291.52
    2652 2345.93  2711.7 2354.26  2731.6 2352.78  2791.2 2362.32  2880.6 2332.37
#Mann= 3 , 0 , 0
       0     .06       0  1184.3    .045       0  1299.3     .06       0
Bank Sta=1184.3,1299.3
XS Rating Curve= 0 ,0
Exp/Cntr=0.3,0.1

Type RM Length L Ch R = 1 ,83314.8 ,1405.5,1403,1400.4
XS GIS Cut Line= 4
     2220834.742      352926.483     2220307.181      353683.141
     2219676.972      354631.058     2218774.714      355033.688
#Sta/Elev= 30
       0 2158.41    80.2  2155.2   180.5 2143.46   260.7  2114.1   280.7 2109.88
     381 2072.11   471.2 2052.35   521.4 2051.32   591.6 2043.94   962.7 2041.88
  1033.2 2037.38  1325.4 2036.15  1367.12032.359    1416  2028.3  1482.12032.017
    1547 2037.09  2272.4 2052.27  2312.8 2069.42  2332.9 2082.95  2403.5 2118.17
  2423.6 2136.97  2494.2 2183.11  2574.9  2210.6  2655.5 2218.18  2736.2 2215.82
  2796.7 2217.98  2897.5 2239.82  2917.7 2250.01  2998.3 2278.29  3048.7 2278.15
#Mann= 3 , 0 , 0
       0     .06       0  1367.1    .045       0  1482.1     .06       0
Bank Sta=1367.1,1482.1
XS Rating Curve= 0 ,0
Exp/Cntr=0.3,0.1

Type RM Length L Ch R = 1 ,81911.7 ,1174,1173.7,1173.4
XS GIS Cut Line= 4
     2220859.047      352165.946     2219198.723      353015.865
      2218677.89      354047.115     2218712.528       354941.48
#Sta/Elev= 30
       0 2146.28    20.2 2136.69   110.9 2107.67   181.5 2094.88   211.7 2083.73
   272.2  2078.6   705.8  2065.3   826.8 2056.86   957.8  2056.1  1088.9 2043.61
  1391.4 2036.38  1512.3 2042.97  1582.9    2037    1845 2037.32  2116.4 2032.54
  2136.5 2027.38  2166.6 2024.27  2196.7 2024.69  2216.8 2028.86  3523.4 2041.01
  3533.4 2042.46  3553.5 2052.54  3563.6 2052.75  3654.1 2100.54  3664.2 2102.22
  3744.6 2142.92  3754.7 2143.47  3845.2  2188.7  3855.2 2189.53  3915.6 2218.23
#Mann= 3 , 0 , 0
       0     .06       0  2136.5    .045       0  2216.8     .06       0
Bank Sta=2136.5,2216.8
XS Rating Curve= 0 ,0
Exp/Cntr=0.3,0.1

Type RM Length L Ch R = 1 ,80737.8 ,1663.3,1659.9,1656.4
XS GIS Cut Line= 2
     2218758.161      351317.511     2217197.502      354529.156
#Sta/Elev= 30
       0 2110.87   282.4 2059.31     353 2051.61   443.8 2046.42   776.7 2038.22
   978.4 2038.49    1039 2031.03  1553.4 2028.28  1698.92020.832    1745  2019.1
  1775.3 2019.54  1813.92024.754  2027.5 2028.25  2289.7 2027.86  2370.4 2035.42
    2552 2037.96  2683.1 2066.83  2723.5 2079.32  2753.7 2092.04  2814.2 2109.04
  2935.3 2107.13  3066.4 2131.53  3167.3 2136.62    3248 2137.17  3328.7  2128.3
  3379.1 2117.16  3419.5  2100.5  3439.6 2096.31  3490.1 2075.46  3570.8 2069.23
#Mann= 3 , 0 , 0
       0     .06       0  1698.9    .045       0  1813.9     .06       0
#XS Ineff= 2 , 0
                         2016.04         2028.17
Permanent Ineff=
       F       F
Bank Sta=1698.9,1813.9
XS Rating Curve= 0 ,0
Exp/Cntr=0.3,0.1

Type RM Length L Ch R = 1 ,79077.9 ,1840.3,1857.9,1875.4
XS GIS Cut Line= 4
     2217673.784      351005.589     2216539.112      352153.841
     2216289.789      352953.431     2215438.896      353764.279
#Sta/Elev= 30
       0 2037.03   585.2 2022.68  2058.3 2021.52  2104.52015.228  2118.8 2014.87
  2159.2  2014.9  2179.4  2017.7  2199.6 2020.74  2320.7 2022.42    2472 2032.25
  2572.4 2040.97    2713 2057.79  2763.3 2075.13  2883.8 2123.48  2934.1  2157.8
  2954.2 2176.21  3004.4 2210.22  3024.5 2218.22  3054.6 2237.29  3064.7 2240.52
  3104.8  2242.4  3155.1 2240.85  3225.4 2245.74  3255.5 2252.09  3285.7 2262.02
  3325.8 2270.46  3345.9 2270.58  3466.5 2299.92  3506.7  2301.1  3627.2 2320.72
#Mann= 3 , 0 , 0
       0     .06       0  2104.5    .045       0  2179.4     .06       0
Bank Sta=2104.5,2179.4
XS Rating Curve= 0 ,0
Exp/Cntr=0.3,0.1

Type RM Length L Ch R = 1 ,77220   ,1597.6,1591.9,1586.2
XS GIS Cut Line= 2
     2217178.048      350287.366     2214103.406      352028.522
#Sta/Elev= 30
       0 2088.27    50.5 2076.41   242.3  2068.1   292.8 2048.62   333.2  2029.1
   353.3  2024.4  1150.9 2017.91  1413.4 2012.15  1665.8 2015.36  1767.42012.017
  1807.1 2010.37  1857.6 2010.76  1882.42013.547    1908 2015.73  2332.1 2017.48
  2453.2 2020.56  2554.2 2026.82  2604.6 2041.42  2624.8 2044.13    2958 2050.79
  3048.8    2067  3079.1 2070.11  3089.2 2074.61  3129.6 2105.08  3190.2 2139.62
  3210.4 2155.91  3301.2 2208.84  3341.6 2217.39  3472.8  2232.7  3533.4 2246.65
#Mann= 3 , 0 , 0
       0     .06       0  1767.4    .045       0  1882.4     .06       0
Bank Sta=1767.4,1882.4
XS Rating Curve= 0 ,0
Exp/Cntr=0.3,0.1

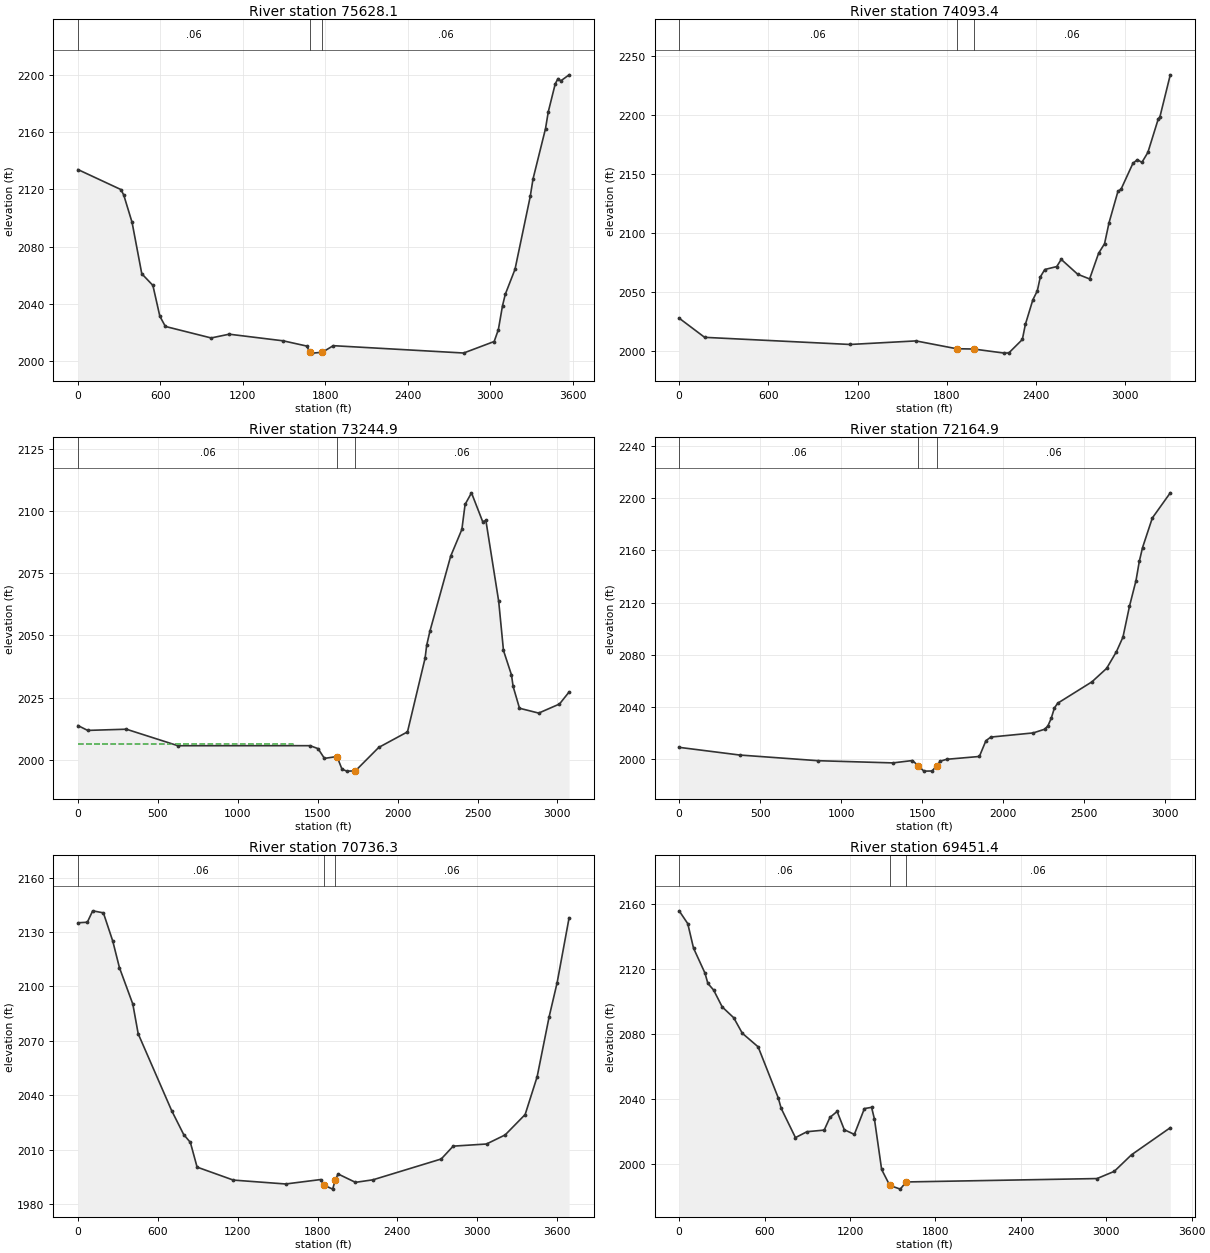
Type RM Length L Ch R = 1 ,75628.1 ,1527.8,1534.3,1540.7
XS GIS Cut Line= 2
     2215997.809      348653.976      2213427.89      351135.657
#Sta/Elev= 30
       0 2133.82   312.8 2119.83     333    2116   393.6 2096.88   464.2 2060.97
     545 2052.82   595.4 2031.32   635.8 2024.12   968.8 2016.08    1100 2018.71
  1493.6 2014.06  1665.2 2010.39  1685.4 2006.02  1705.6 2005.47  1777.52006.062
  1856.9 2010.68  2805.6 2005.55  3027.6  2013.6  3057.9 2021.85  3088.2  2038.6
  3108.3  2046.6    3179 2064.06    3290 2115.06  3310.2 2127.29    3401 2162.45
  3421.2 2174.24  3471.6  2193.7  3491.8 2197.47    3512 2195.83  3572.6 2200.07
#Mann= 3 , 0 , 0
       0     .06       0  1685.4    .045       0  1777.5     .06       0
Bank Sta=1685.4,1777.5
XS Rating Curve= 0 ,0
Exp/Cntr=0.3,0.1

Type RM Length L Ch R = 1 ,74093.4 ,844.4,848.7,853
XS GIS Cut Line= 3
     2215089.348      348245.032     2213011.223      349401.282
     2212443.515      350130.449
#Sta/Elev= 30
       0 2027.82   171.3 2011.56  1148.8 2005.51  1592.1 2008.53  1865.12001.905
  1980.1 2001.65  2186.7 1998.17  2216.9 1998.37  2307.6 2009.74  2327.8  2022.5
  2378.1 2043.34  2408.3 2051.02  2428.4 2062.79  2458.5 2069.07  2538.8 2071.56
    2569 2077.66  2679.5 2065.06  2759.8 2061.07  2820.1  2082.8  2860.3 2090.96
  2890.4 2108.72  2950.7  2135.5  2970.8 2137.06  3051.1 2159.12  3081.3  2162.2
  3111.4 2159.87  3151.6 2168.34  3221.9 2196.92  3231.9 2198.18  3302.2 2234.12
#Mann= 3 , 0 , 0
       0     .06       0  1865.1    .045       0  1980.1     .06       0
#XS Ineff= 2 , 0
         1579.61 2007.97
Permanent Ineff=
       F       F
Bank Sta=1865.1,1980.1
XS Rating Curve= 0 ,0
Exp/Cntr=0.3,0.1

Type RM Length L Ch R = 1 ,73244.9 ,1083.8,1080.2,1076.6
XS GIS Cut Line= 4
      2214686.11      347953.492     2213392.615      348381.455
     2212828.181      348550.756     2211713.433      348672.997
#Sta/Elev= 30
       0 2013.79    60.6 2011.84   302.8 2012.32   625.7 2005.68  1452.3  2005.7
  1502.3 2004.51  1542.2 2000.59  1620.72001.331  1652.1 1996.26  1682.1 1995.47
  1735.71995.557  1881.8 2004.99  2061.9 2011.25    2172 2040.87    2182 2046.04
    2202 2051.66  2332.2 2081.88  2402.3 2092.65  2422.3 2102.67  2462.4 2107.34
  2532.5 2095.74  2552.5 2096.23  2632.6 2063.73  2662.6 2043.97  2712.7 2034.13
  2722.7 2029.56  2762.8 2020.75  2882.9  2018.8  3013.1 2022.45  3073.2 2027.29
#Mann= 3 , 0 , 0
       0     .06       0  1620.7    .045       0  1735.7     .06       0
#XS Ineff= 2 , 0
         1343.07 2006.22
Permanent Ineff=
       F       F
Bank Sta=1620.7,1735.7
XS Rating Curve= 0 ,0
Exp/Cntr=0.3,0.1

Type RM Length L Ch R = 1 ,72164.9 ,1435.7,1428.4,1421.1
XS GIS Cut Line= 2
     2214046.191      346815.504     2211322.421      348148.289
#Sta/Elev= 30
       0 2008.91   372.8 2003.03   856.3 1998.67  1319.7 1996.97  1440.6 1998.79
  1474.4 1994.97  1511.2 1990.66  1561.5 1990.77  1589.41994.703  1611.9 1998.29
  1652.2 1999.74  1853.7 2001.91    1894 2013.99  1924.2 2016.79  2186.1 2019.98
  2256.6 2022.81  2276.8 2025.38  2296.9 2031.05  2317.1 2039.15  2337.2 2042.78
  2548.8  2059.2  2639.5 2069.53  2699.9 2082.33  2740.2 2093.49  2780.5 2117.19
  2820.8 2136.92    2841 2151.56  2861.1  2162.2  2921.6 2184.94  3032.4 2204.24
#Mann= 3 , 0 , 0
       0     .06       0  1474.4    .045       0  1589.4     .06       0
Bank Sta=1474.4,1589.4
XS Rating Curve= 0 ,0
Exp/Cntr=0.3,0.1

Type RM Length L Ch R = 1 ,70736.3 ,1282.5,1284.9,1287.3
XS GIS Cut Line= 4
     2213633.119      345223.838     2212850.386      345513.299
     2211552.949      346649.788     2210458.451      346936.028
#Sta/Elev= 30
       0 2135.12    70.4 2135.43   110.6 2141.72     191  2140.6   261.4 2125.02
   311.7 2110.34   412.2 2090.24   452.5 2073.87   703.8  2031.5   794.3 2018.28
   844.6 2013.92   895.1 2000.29  1167.4 1993.13  1560.8 1990.98    1823 1993.42
  1851.61990.246  1913.8 1988.14    1934 1993.24  1954.2 1996.52  2085.3 1991.88
  2216.4 1993.28  2729.5 2004.77  2819.6 2011.86  3069.9 2013.04  3210.1 2018.06
  3360.3 2029.31  3450.4 2050.15  3540.5 2083.23  3600.6 2102.06  3690.6 2137.88
#Mann= 3 , 0 , 0
       0     .06       0  1851.6    .045       0    1934     .06       0
Bank Sta=1851.6,1934
XS Rating Curve= 0 ,0
Exp/Cntr=0.3,0.1

Type RM Length L Ch R = 1 ,69451.4 ,1661.1,1651.8,1642.4
XS GIS Cut Line= 2
     2212934.567      344179.034     2210221.323      346309.572
#Sta/Elev= 30
       0 2155.83    60.5 2147.93   100.9 2132.88   181.6 2117.42   201.7 2111.11
   242.1 2107.02   302.6 2096.61   383.3 2089.96   443.8 2080.39   554.8 2072.03
     696 2040.63   716.2 2034.22     817  2016.1   897.8 2019.75  1018.8 2020.74
  1059.1 2028.54  1109.6 2032.23    1160 2020.97  1230.6 2018.08  1301.2 2033.99
  1351.7 2034.76  1371.8 2027.51  1422.3 1996.48  1479.41986.669  1553.4 1984.37
  1594.41988.791  2935.3 1990.88  3056.4 1995.32  3177.4 2005.53  3449.8 2022.21
#Mann= 3 , 0 , 0
       0     .06       0  1479.4    .045       0  1594.4     .06       0
Bank Sta=1479.4,1594.4
XS Rating Curve= 0 ,0
Exp/Cntr=0.3,0.1

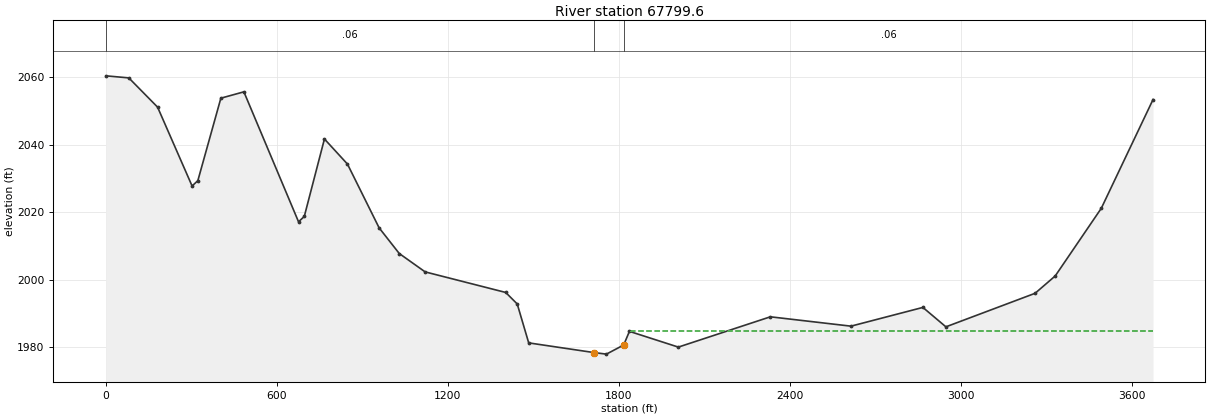
Type RM Length L Ch R = 1 ,67799.6 ,2266.2,2262,2258.4
XS GIS Cut Line= 2
     2211158.617      342794.594     2209425.094      346035.621
#Sta/Elev= 30
       0 2060.37    80.8 2059.76   181.8  2051.1   302.9 2027.75   323.1 2029.33
   403.9 2053.75   484.7 2055.63   676.5 2017.15   696.7 2018.74   767.4 2041.67
   848.2 2034.24   959.3 2015.36    1030 2007.76  1120.8 2002.32  1403.6 1996.23
    1444 1992.82  1484.3  1981.3  1714.41978.417    1757 1977.97  1817.6 1980.67
  1837.8 1984.71  2009.4 1980.05  2332.5 1989.02  2615.3 1986.25  2867.7  1991.8
  2948.5 1986.05  3261.5 1995.98  3332.2 2001.12  3493.8 2021.14  3675.5 2053.36
#Mann= 3 , 0 , 0
       0     .06       0  1714.4    .045       0  1817.6     .06       0
#XS Ineff= 2 , 0
                         1842.96         1984.71
Permanent Ineff=
       F       F
Bank Sta=1714.4,1817.6
XS Rating Curve= 0 ,0
Exp/Cntr=0.3,0.1