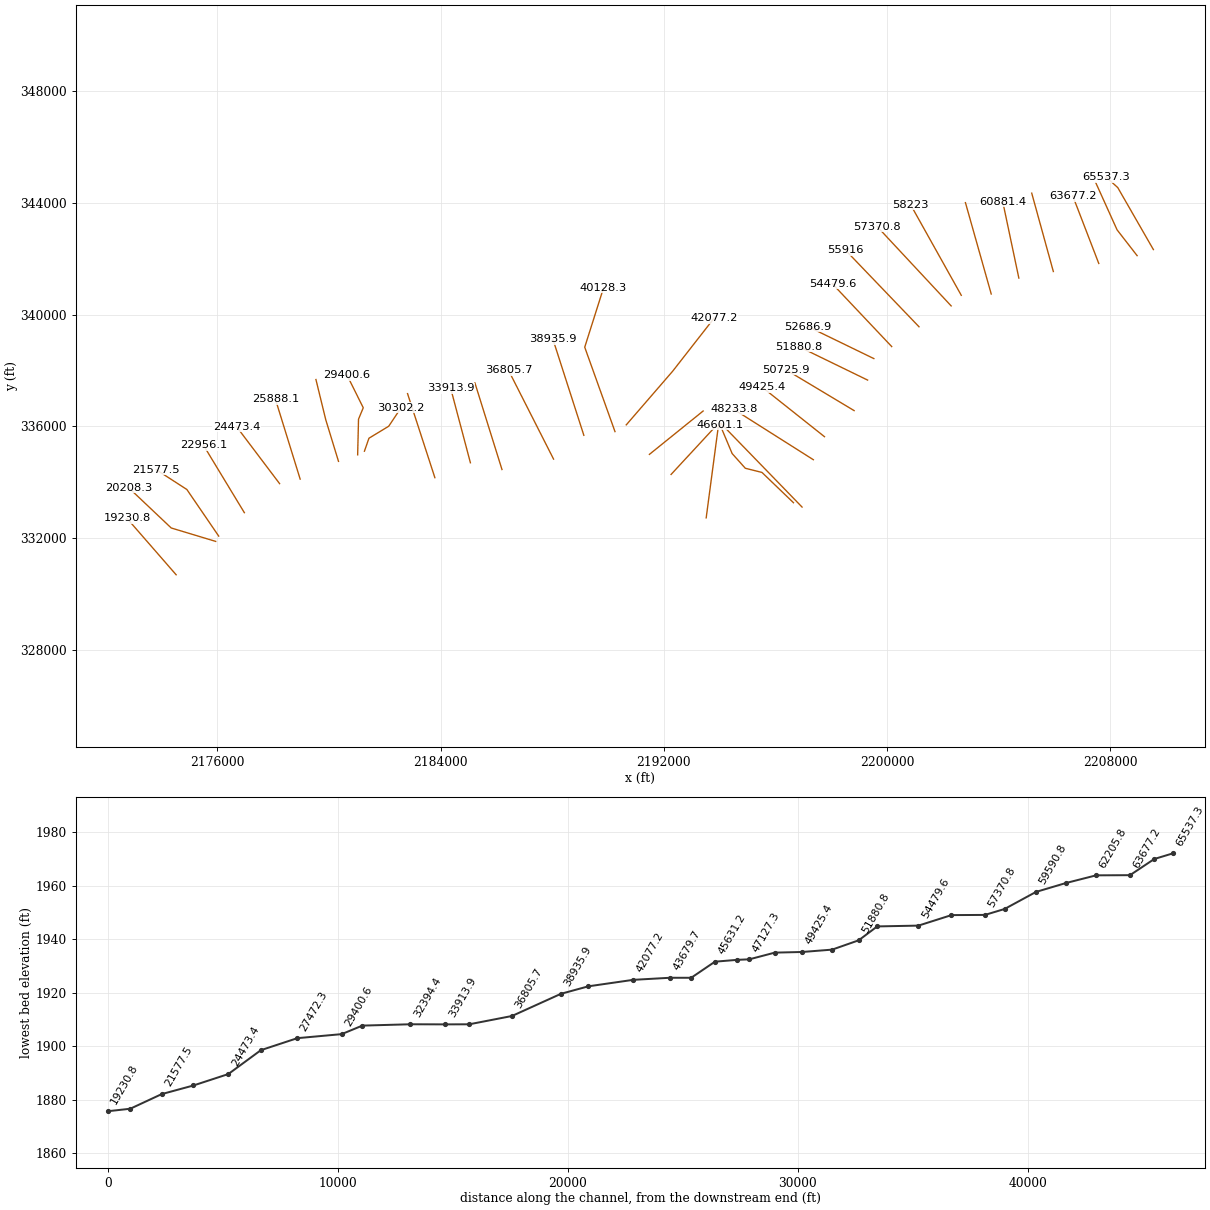
HEC-RAS study AntCk.prj: AntCk

--- AntCk.g01 (geometry) --- (continued)

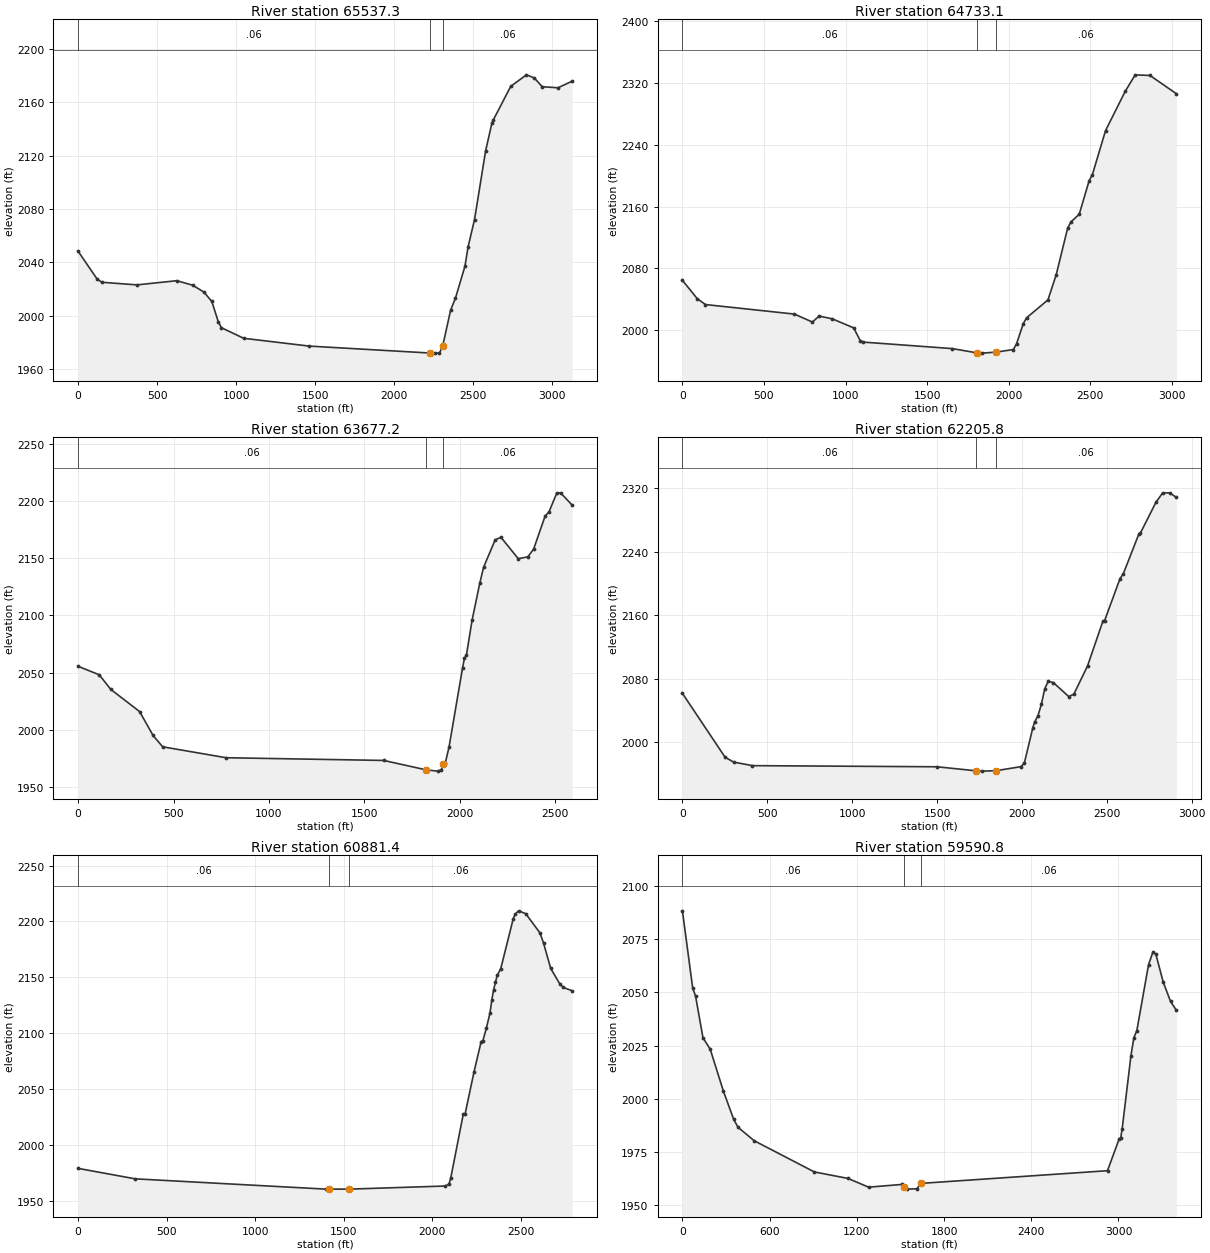
Type RM Length L Ch R = 1 ,65537.3 ,801.4,804.2,806.2
XS GIS Cut Line= 3
     2209537.265      342323.157     2208261.223      344541.907
     2207842.048      344923.997
#Sta/Elev= 30
       0 2048.41   120.9 2027.46   151.2 2025.16   372.8 2023.21   624.8 2026.34
   725.5 2022.95   796.1 2017.81   846.4 2010.77   886.8 1995.73   906.9 1991.13
    1048 1983.19  1461.1 1977.36  2225.11972.158  2257.2 1972.07  2287.4 1972.16
  2307.6 1977.32    2358 2004.36  2388.2 2013.16  2448.7 2037.26  2468.8 2051.91
  2509.1 2072.09  2579.4 2123.66  2619.2 2144.41  2629.2 2147.07  2738.6    2172
  2838.1  2180.6  2887.9 2178.25  2937.6  2171.7  3037.2 2170.89  3126.7 2175.82
#Mann= 3 , 0 , 0
       0     .06       0  2225.1    .045       0  2307.6     .06       0
Bank Sta=2225.1,2307.6
XS Rating Curve= 0 ,0
Exp/Cntr=0.3,0.1

Type RM Length L Ch R = 1 ,64733.1 ,1057,1055.8,1054.6
XS GIS Cut Line= 3
     2208953.672      342107.106     2208235.181       343031.49
     2207469.556      344724.199
#Sta/Elev= 30
       0 2064.35    90.8 2040.61   141.3 2032.94   686.3 2020.59   797.3 2010.22
   837.7 2018.01   918.4 2014.48  1049.7 2002.74    1090  1986.3  1110.2 1984.25
  1655.4 1975.84  1806.81970.273  1837.2 1969.98  1921.81971.247    2029 1974.63
  2049.2  1982.4  2089.6 2008.08  2109.8 2015.74    2241 2038.93  2291.5 2071.32
  2362.2 2132.24  2382.4 2140.08  2432.9 2149.98  2493.4 2193.24  2513.6 2201.32
  2594.4 2258.46  2715.6 2309.55  2776.2 2330.68    2867 2329.82  3028.6 2306.18
#Mann= 3 , 0 , 0
       0     .06       0  1806.8    .045       0  1921.8     .06       0
Bank Sta=1806.8,1921.8
XS Rating Curve= 0 ,0
Exp/Cntr=0.3,0.1

Type RM Length L Ch R = 1 ,63677.2 ,1473.2,1471.2,1469.2
XS GIS Cut Line= 2
     2207580.147      341827.745     2206648.943      344243.054
#Sta/Elev= 30
       0 2055.58   110.8 2048.15   171.2 2035.37   322.3 2016.01   392.8 1995.11
   443.2  1985.2   775.6 1975.64  1601.5 1973.27  1823.41965.052  1883.5 1963.93
  1903.7 1965.11  1913.8  1970.4  1923.8 1970.71    1944 1985.16  2014.5 2054.08
  2024.6 2062.72  2034.6 2065.04  2064.8  2096.1  2105.1 2128.41  2125.3 2142.35
  2185.7 2166.18  2215.9 2168.34  2306.6 2149.65  2356.9 2151.26  2387.2 2158.11
  2447.6 2187.03  2467.7 2190.58    2508 2206.88  2528.2 2207.23  2588.6 2196.57
#Mann= 3 , 0 , 0
       0     .06       0  1823.4    .045       0  1913.8     .06       0
Bank Sta=1823.4,1913.8
XS Rating Curve= 0 ,0
Exp/Cntr=0.3,0.1

Type RM Length L Ch R = 1 ,62205.8 ,1329.5,1324.5,1319.6
XS GIS Cut Line= 2
     2205952.299      341538.974     2205178.236      344344.225
#Sta/Elev= 30
       0 2061.69   251.7 1981.26   302.1 1975.22   412.8 1970.76  1500.4 1969.34
  1731.41964.229  1762.2 1963.87  1846.41964.379  1993.8 1969.46  2013.9 1973.64
  2064.2 2018.27  2074.3 2025.47  2094.5 2033.51  2114.6 2047.75  2134.7 2067.42
  2154.9 2076.83  2185.1 2075.24  2275.7  2057.7  2305.9 2060.64  2386.5 2096.08
  2477.1 2152.42  2487.2 2153.12  2577.8 2205.88  2597.9 2212.33  2688.6  2261.9
  2698.6 2263.48  2789.2  2301.8  2829.5 2313.88  2869.8 2313.76  2910.1 2308.22
#Mann= 3 , 0 , 0
       0     .06       0  1731.4    .045       0  1846.4     .06       0
Bank Sta=1731.4,1846.4
XS Rating Curve= 0 ,0
Exp/Cntr=0.3,0.1

Type RM Length L Ch R = 1 ,60881.4 ,1285.6,1290.5,1295.3
XS GIS Cut Line= 2
     2204716.696      341303.943     2204140.514      344033.533
#Sta/Elev= 30
       0  1979.5   322.3 1970.16  1399.9 1960.97  1416.1 1960.97  1531.1 1960.97
  2074.7 1963.75  2094.8 1965.65  2104.9 1971.24  2175.4 2028.13  2185.5 2028.12
  2235.8  2065.6  2276.1 2092.72  2286.2 2093.69  2306.3 2105.14  2326.5 2118.55
  2336.5  2130.1  2346.6  2139.1  2356.7 2145.56  2366.8 2151.78  2386.9 2157.92
  2457.4 2202.46  2467.5 2206.36  2487.6 2209.52  2527.9 2206.96  2608.5 2189.76
  2628.6 2180.68  2668.9  2158.1  2719.2 2144.53  2739.4 2141.11  2789.7 2138.18
#Mann= 3 , 0 , 0
       0     .06       0  1416.1    .045       0  1531.1     .06       0
Bank Sta=1416.1,1531.1
XS Rating Curve= 0 ,0
Exp/Cntr=0.3,0.1

Type RM Length L Ch R = 1 ,59590.8 ,1362.5,1367.6,1372.7
XS GIS Cut Line= 2
     2203727.292      340733.581     2202803.613      344003.944
#Sta/Elev= 30
       0 2088.24    70.6 2052.05    90.8 2048.11   141.2 2028.76   191.6 2023.23
   282.4 2003.55   352.9 1990.38   383.2 1986.64   494.1 1980.36   907.6 1965.74
  1139.5 1962.68  1280.7 1958.59  1512.6 1959.88  1525.51958.662  1542.8 1957.67
  1613.4 1957.85  1640.51960.363  2924.4 1966.32    3005  1981.3  3015.1 1981.67
  3025.2  1985.9  3085.7 2020.28  3105.9 2028.77    3126 2031.96  3206.7 2062.96
    3237 2068.92  3257.1 2067.89  3307.6 2054.81    3358 2045.76  3398.3 2041.59
#Mann= 3 , 0 , 0
       0     .06       0  1525.5    .045       0  1640.5     .06       0
Bank Sta=1525.5,1640.5
XS Rating Curve= 0 ,0
Exp/Cntr=0.3,0.1

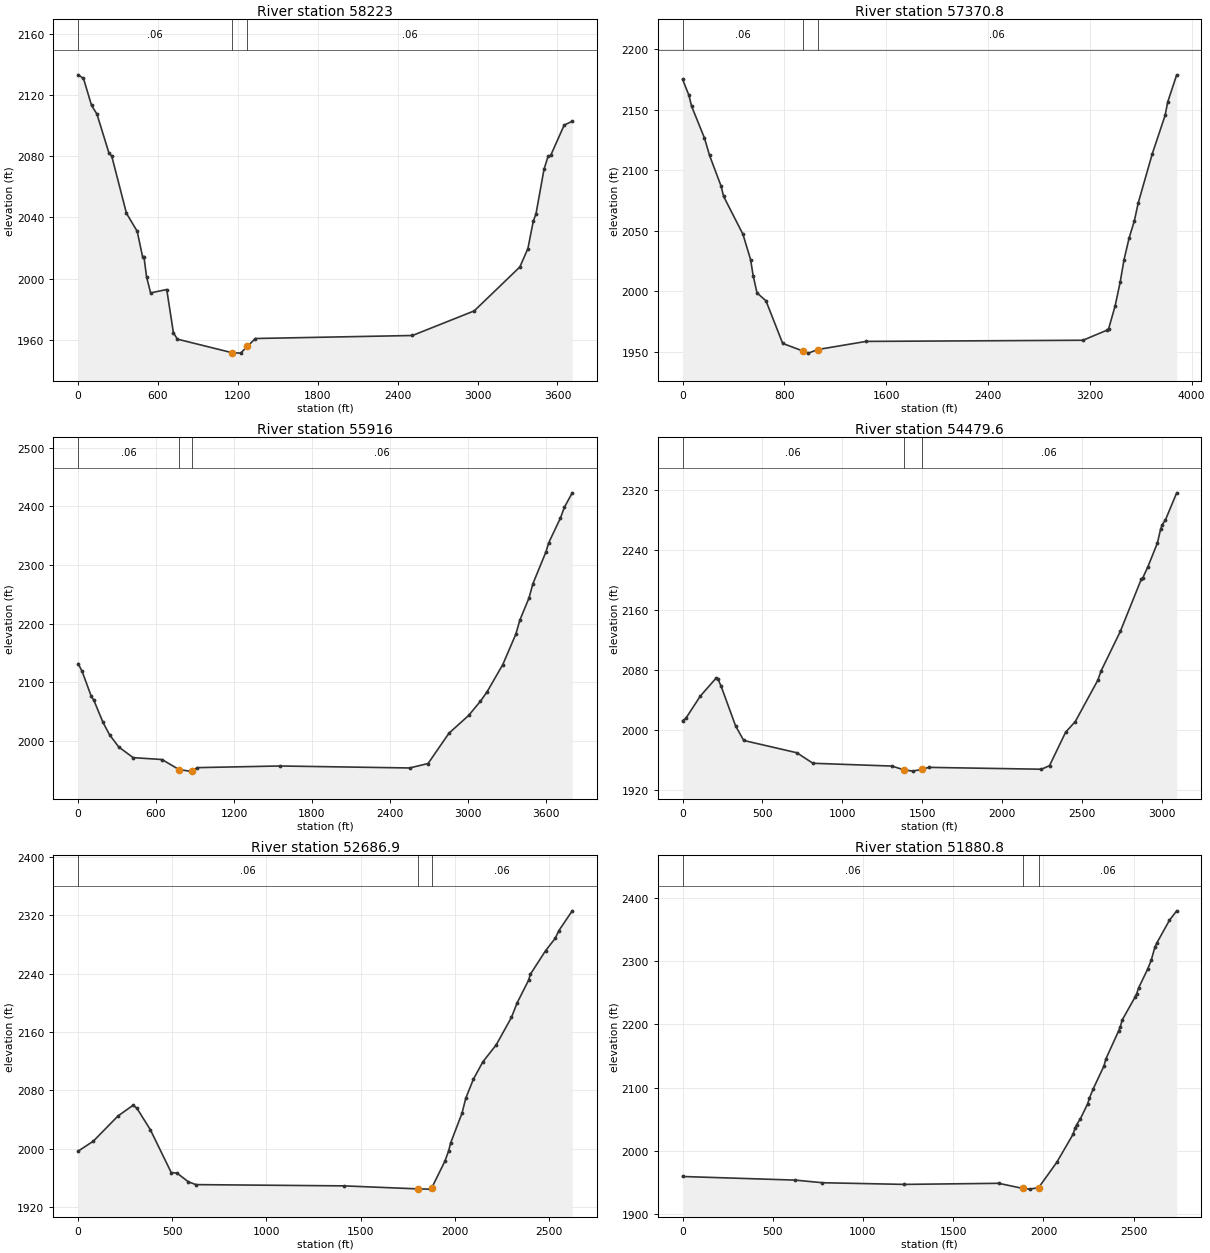
Type RM Length L Ch R = 1 ,58223   ,846.6,852.3,857.9
XS GIS Cut Line= 2
     2202653.797      340687.811     2200841.583      343925.843
#Sta/Elev= 30
       0 2133.11    40.3 2130.78   100.8 2113.12   141.2 2107.49   231.9 2081.91
   252.1 2080.14     363 2042.64   443.7 2030.87     484  2014.3   494.1 2014.39
   514.2 2001.01   544.5 1990.62   665.5 1992.85   715.9 1964.45   746.2  1960.4
  1155.51951.573  1220.1 1951.28  1270.5 1955.65    1331 1960.83  2510.7  1962.8
  2974.6 1978.87  3317.4 2007.58  3377.9 2019.62  3418.2 2037.53  3438.4 2042.18
  3498.9 2071.43  3529.2 2079.81  3549.3 2080.53  3650.2 2100.25  3710.7 2102.78
#Mann= 3 , 0 , 0
       0     .06       0  1155.5    .045       0  1270.5     .06       0
Bank Sta=1155.5,1270.5
XS Rating Curve= 0 ,0
Exp/Cntr=0.3,0.1

Type RM Length L Ch R = 1 ,57370.8 ,1454.2,1455,1455.8
XS GIS Cut Line= 2
     2202292.473      340307.532     2199643.214      343145.497
#Sta/Elev= 30
       0 2174.87    50.4 2161.62    70.6 2152.78   171.4 2126.64   211.8 2112.22
   302.5 2086.86   322.7 2078.29     474 2047.22   534.4 2026.24   554.6    2013
   584.9 1998.77   655.5 1992.18   786.6  1957.1   948.11950.716   988.2 1949.07
  1063.11952.052    1442 1958.74  3146.2 1959.69  3337.8 1968.14  3347.9 1969.24
  3398.3 1987.82  3438.6 2007.69  3468.9 2026.27  3509.2 2044.25  3549.6 2058.05
  3579.8 2072.79  3690.8 2113.53  3791.6 2145.19  3811.8 2156.14  3882.4 2178.62
#Mann= 3 , 0 , 0
       0     .06       0   948.1    .045       0  1063.1     .06       0
Bank Sta=948.1,1063.1
XS Rating Curve= 0 ,0
Exp/Cntr=0.3,0.1

Type RM Length L Ch R = 1 ,55916   ,1435.3,1436.1,1436.9
XS GIS Cut Line= 2
     2201140.369      339560.977     2198505.307      342304.293
#Sta/Elev= 30
       0 2132.09    30.3 2119.28   100.9 2076.59   121.1 2069.72   191.7 2031.94
   242.2 2010.95   312.8 1990.16   423.8 1971.98   645.8 1968.77   776.9 1951.67
   857.6    1949   876.31949.606   918.2 1954.96  1553.8 1957.76  2552.7 1954.38
    2694 1961.98  2855.4  2013.7  3006.8  2043.9  3097.6 2068.24    3148 2083.95
  3269.1 2130.42    3370 2182.43  3400.3 2205.96  3470.9 2243.91  3501.2 2268.27
  3602.1 2322.74  3622.2 2337.67    3713 2380.09  3743.3 2398.34  3803.9 2423.04
#Mann= 3 , 0 , 0
       0     .06       0   776.9    .045       0   876.3     .06       0
Bank Sta=776.9,876.3
XS Rating Curve= 0 ,0
Exp/Cntr=0.3,0.1

Type RM Length L Ch R = 1 ,54479.6 ,1783.1,1792.6,1801
XS GIS Cut Line= 2
     2200161.489      338852.867     2198035.311      341100.242
#Sta/Elev= 30
       0 2012.57    20.2 2015.48   110.8 2045.26   211.6 2069.72   221.7 2068.03
   241.9 2058.16   332.6 2005.17   382.9 1986.05   715.5 1969.61   816.3 1955.56
  1310.1 1951.84  1383.41946.985  1441.1 1945.07  1498.41947.439  1541.8  1950.1
  2247.3 1947.61  2297.6 1952.41  2398.4 1997.02  2458.9 2011.29    2600 2066.51
  2620.1 2078.79    2741 2131.78    2872 2201.33  2882.1 2203.51  2912.4 2217.45
  2972.8 2249.59    2993 2268.08  3003.1 2273.98  3023.2 2280.49  3093.8 2316.81
#Mann= 3 , 0 , 0
       0     .06       0  1383.4    .045       0  1498.4     .06       0
Bank Sta=1383.4,1498.4
XS Rating Curve= 0 ,0
Exp/Cntr=0.3,0.1

Type RM Length L Ch R = 1 ,52686.9 ,806.1,806.4,806.7
XS GIS Cut Line= 2
     2199521.616      338422.504     2197161.418      339568.397
#Sta/Elev= 30
       0 1996.83    80.7 2010.51   211.9 2045.11   292.6 2059.87   312.8  2055.4
   383.5 2026.21   494.5 1967.45   524.7 1966.82   585.3 1954.83   625.6 1950.96
  1412.7 1949.23    18041945.105  1866.8 1944.77  1876.9 1946.07  1947.6 1983.06
  1967.8 1997.52  1977.8 2007.89  2038.4 2048.86  2058.6 2069.46  2098.9 2095.51
  2149.4 2119.35    2220 2142.51  2300.8 2180.08    2331 2200.03  2391.6 2230.98
  2401.7 2239.45  2482.4 2271.69  2532.8 2288.39    2553 2299.25  2623.7 2326.27
#Mann= 3 , 0 , 0
       0     .06       0    1804    .045       0  1876.9     .06       0
Bank Sta=1804,1876.9
XS Rating Curve= 0 ,0
Exp/Cntr=0.3,0.1

Type RM Length L Ch R = 1 ,51880.8 ,1156.3,1154.6,1153
XS GIS Cut Line= 2
     2199299.278      337652.874     2196836.464      338850.076
#Sta/Elev= 30
       0 1959.55   624.2 1953.83   775.2 1949.69  1228.2 1947.05  1751.8 1948.76
  1884.31940.769  1922.9 1939.57  1973.2 1941.91  2073.9 1981.99  2164.5 2026.52
  2174.6 2035.63  2184.7 2041.75  2204.8 2050.91  2245.1 2074.54  2255.1 2083.77
  2275.3 2097.87  2335.7 2134.55  2345.8 2145.38  2416.2 2189.48  2426.3 2196.69
  2436.4 2207.04  2506.8 2242.82  2516.9 2248.68    2527 2257.57  2577.3 2287.34
  2597.4  2301.6  2617.6 2322.19  2627.6 2328.41  2698.1 2364.72  2738.4 2379.69
#Mann= 3 , 0 , 0
       0     .06       0  1884.3    .045       0  1973.2     .06       0
Bank Sta=1884.3,1973.2
XS Rating Curve= 0 ,0
Exp/Cntr=0.3,0.1

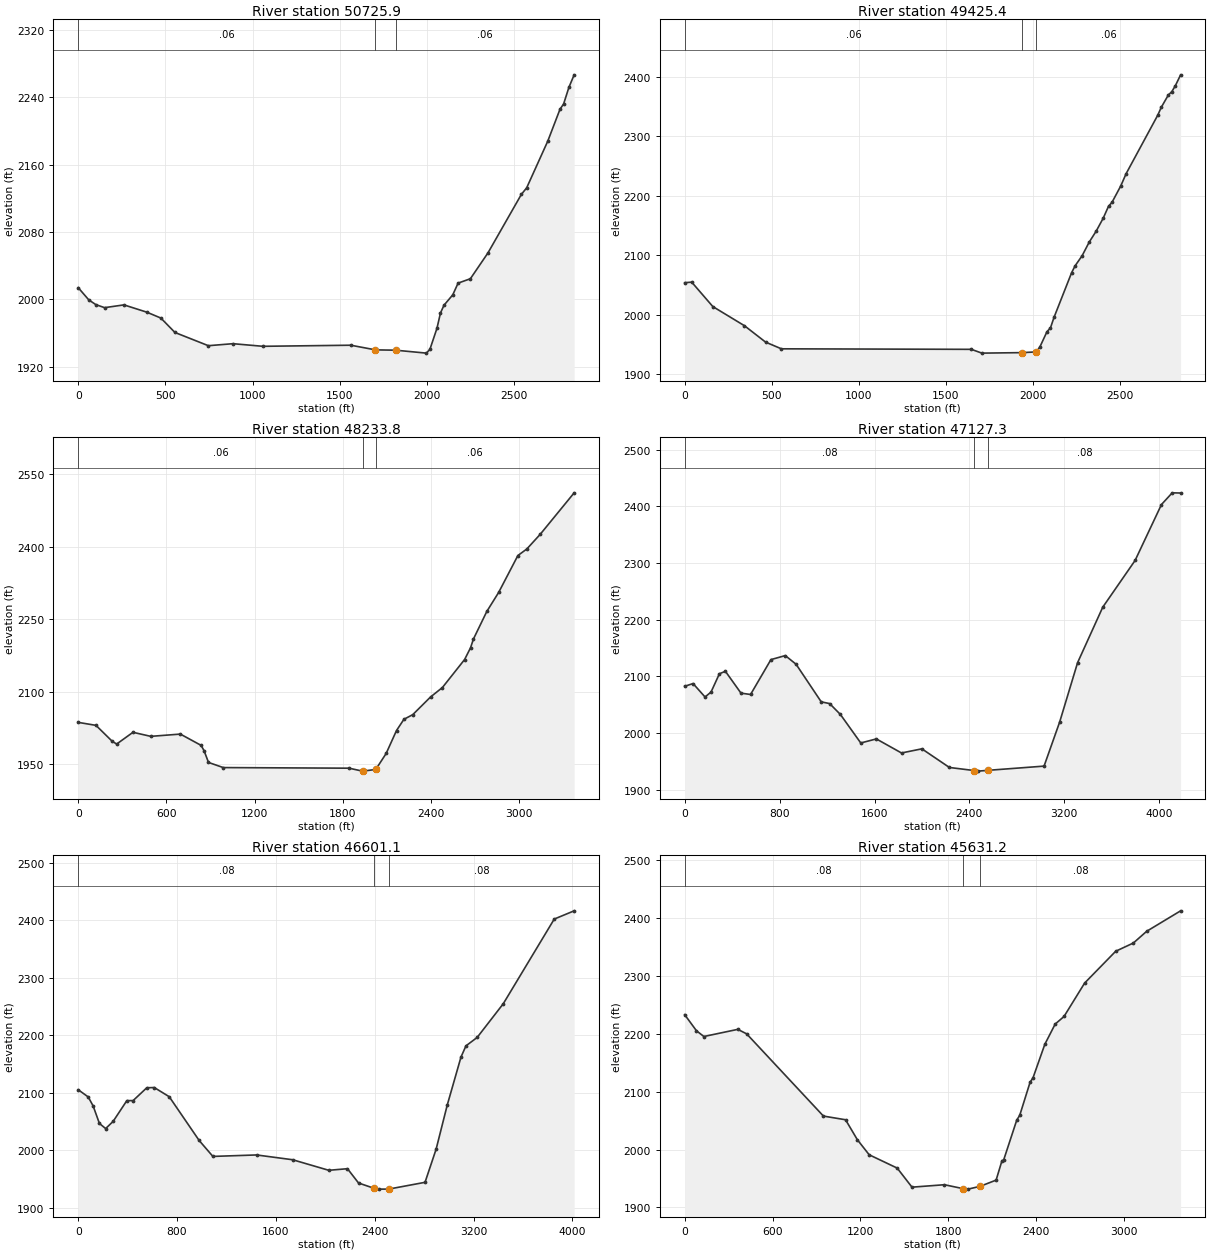
Type RM Length L Ch R = 1 ,50725.9 ,1302.4,1300.5,1298.5
XS GIS Cut Line= 2
     2198815.194      336560.625     2196376.605      338021.451
#Sta/Elev= 30
       0 2013.84    60.5 1999.34   100.8 1993.71   151.2 1990.08   262.1 1993.37
   393.1 1984.74   473.8 1977.73   554.4 1960.62     746 1944.91   887.1  1947.3
  1058.4 1944.19  1562.5 1945.48  1703.81939.964  1818.81939.578  1995.9 1936.09
  2016.1 1940.69  2056.4 1965.64  2076.6 1983.82  2096.7 1992.99  2147.1 2005.36
  2177.4 2019.22  2247.9 2024.43  2348.7 2055.12  2540.2 2124.63  2570.5 2132.35
  2691.5 2187.84    2762 2225.94  2782.2 2231.88  2812.4 2251.58  2842.7 2266.57
#Mann= 3 , 0 , 0
       0     .06       0  1703.8    .045       0  1818.8     .06       0
Bank Sta=1703.8,1818.8
XS Rating Curve= 0 ,0
Exp/Cntr=0.3,0.1

Type RM Length L Ch R = 1 ,49425.4 ,1190.5,1191.6,1192.7
XS GIS Cut Line= 2
     2197753.972      335626.659     2195523.648      337395.726
#Sta/Elev= 30
       0  2053.7    40.4 2054.63   161.5 2013.56   343.2  1981.3   464.4 1953.74
   555.2 1942.46  1645.5 1941.58    1706 1935.21  1938.71936.057    2019 1937.28
  2039.2 1945.83  2079.5  1971.2  2099.7 1977.71  2119.9 1995.26  2220.9  2070.4
    2241 2082.07  2281.4 2099.09  2321.8 2121.88  2362.2 2140.52  2402.6 2162.36
  2432.8 2182.22    2453 2188.95  2503.5 2216.69  2533.8 2237.07  2715.5 2335.51
  2735.7 2348.75  2776.1 2369.38  2796.3 2375.14  2816.5 2385.08  2846.7 2403.38
#Mann= 3 , 0 , 0
       0     .06       0  1938.7    .045       0    2019     .06       0
Bank Sta=1938.7,2019
XS Rating Curve= 0 ,0
Exp/Cntr=0.3,0.1

Type RM Length L Ch R = 1 ,48233.8 ,1111.6,1106.5,1101.4
XS GIS Cut Line= 2
     2197354.369      334802.979     2194502.558      336607.186
#Sta/Elev= 30
       0 2036.04   120.9 2029.85   231.7  1996.7   261.9 1991.16   372.7 2015.47
   493.6 2007.07   695.1 2011.76   836.1 1988.39   856.2 1977.46   886.5 1952.98
   987.2 1942.33  1843.4 1941.07  1934.1 1934.97  1937.9 1934.97  2024.8 1938.46
  2095.3 1971.55  2165.8 2019.14  2216.2 2042.39  2276.6 2052.13  2397.5 2088.71
  2478.1 2108.28  2629.2 2166.35  2669.5  2190.6  2689.6 2209.04  2780.3 2266.05
  2860.9 2305.46  2991.8 2381.97  3052.3 2395.44  3142.9 2425.64  3374.6 2511.94
#Mann= 3 , 0 , 0
       0     .06       0  1937.9    .045       0  2024.8     .06       0
Bank Sta=1937.9,2024.8
XS Rating Curve= 0 ,0
Exp/Cntr=0.3,0.1

Type RM Length L Ch R = 1 ,47127.3 ,522.5,526.2,529.8
XS GIS Cut Line= 2
     2196949.771        333108.5     2194036.956      336106.664
#Sta/Elev= 30
       0 2082.32    70.7 2087.13   171.6 2063.42   222.1 2072.12   292.8 2104.48
   343.3 2108.77   474.6  2070.2   555.3 2067.83     727 2129.44   848.1 2136.54
     939 2121.22    1151  2054.8  1221.7 2051.79  1312.6 2032.52  1484.2 1982.19
  1615.5 1989.36  1827.5 1964.53  1999.2 1971.85  2231.4 1938.92  2442.31933.436
  2473.8 1932.47  2557.31933.894  3029.1 1941.32  3160.3 2018.99  3311.8 2124.08
  3523.8 2222.01  3796.4 2304.54  4018.6  2403.3  4109.4 2423.98  4180.1 2423.64
#Mann= 3 , 0 , 0
       0     .08       0  2442.3    .045       0  2557.3     .08       0
Bank Sta=2442.3,2557.3
XS Rating Curve= 0 ,0
Exp/Cntr=0.3,0.1

Type RM Length L Ch R = 1 ,46601.1 ,993.9,969.8,945.8
XS GIS Cut Line= 5
     2196642.574      333263.592     2195514.093      334347.332
     2194917.539       334496.47     2194445.267      335023.426
     2194007.794      336062.424
#Sta/Elev= 30
       0    2105    80.8 2092.55   121.1 2076.71   171.6 2046.43   222.1 2037.54
   282.6 2050.02   393.7 2086.11   444.1 2086.13   555.2 2108.47   615.7 2108.86
   736.9 2092.88   979.1 2016.81  1090.2 1989.12  1443.5 1991.68    1736 1983.34
  2028.3 1964.99  2179.5 1967.77  2269.2 1942.92    23981933.491  2438.6 1932.27
    25131932.308  2807.4 1944.11  2897.2 2001.76  2987.8 2078.87  3098.5 2161.84
  3138.8 2181.33  3229.4 2195.94  3440.7 2254.52  3853.4  2401.7  4014.5 2416.02
#Mann= 3 , 0 , 0
       0     .08       0    2398    .045       0    2513     .08       0
Bank Sta=2398,2513
XS Rating Curve= 0 ,0
Exp/Cntr=0.3,0.1

Type RM Length L Ch R = 1 ,45631.2 ,1046.1,1032.2,1018.3
XS GIS Cut Line= 2
     2193515.637      332721.722     2193961.296      336077.564
#Sta/Elev= 30
       0 2233.25    80.6 2205.36     131 2195.48   362.7 2207.85   423.2 2200.04
   947.1 2057.89  1098.2 2051.52  1178.8 2016.96  1259.4 1990.98  1450.8 1967.94
  1551.6 1934.98  1773.2 1939.19  1902.11932.335  1934.5 1931.58  2017.1 1936.47
  2125.9 1947.17  2166.2 1981.02  2176.3 1981.15  2266.9 2051.02  2287.1 2059.18
  2357.6 2116.29  2377.8  2124.1  2458.4 2182.03  2528.9 2216.93  2589.4  2230.1
  2730.4 2287.99    2942 2342.86  3062.9 2357.17  3153.6  2377.4  3385.3 2412.79
#Mann= 3 , 0 , 0
       0     .08       0  1902.1    .045       0  2017.1     .08       0
Bank Sta=1902.1,2017.1
XS Rating Curve= 0 ,0
Exp/Cntr=0.3,0.1

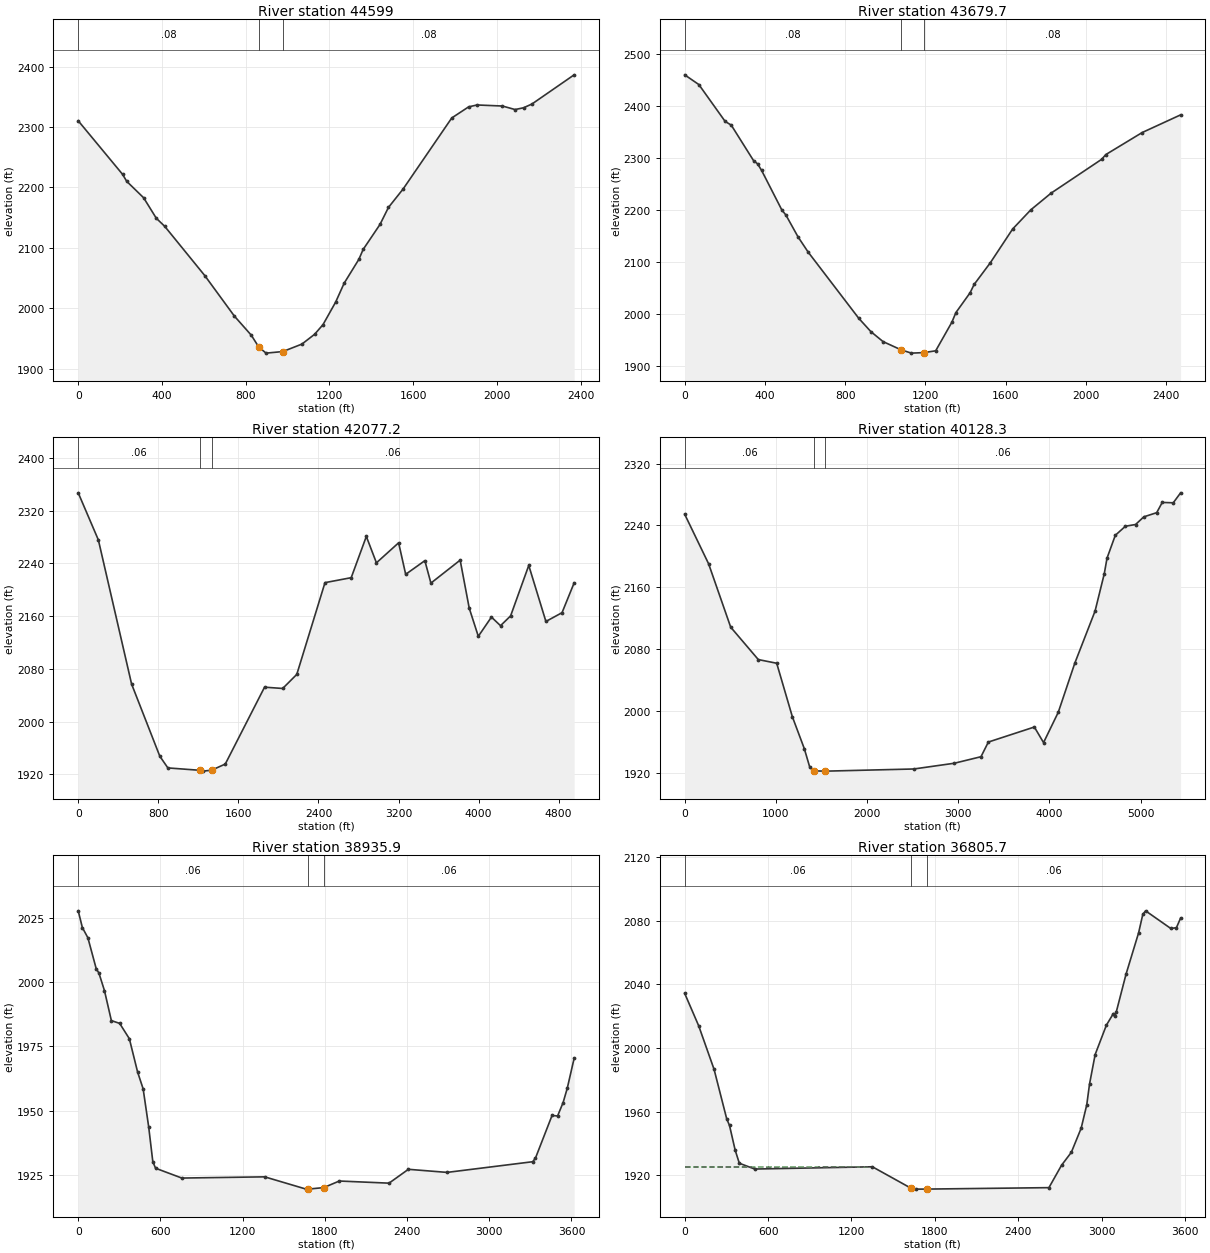
Type RM Length L Ch R = 1 ,44599   ,922.6,919.3,916
XS GIS Cut Line= 2
      2192258.26      334275.931     2193868.176      336013.543
#Sta/Elev= 30
       0 2310.15   211.7 2221.58   231.8 2209.88   312.5 2182.69     373 2148.82
   413.3  2135.4   604.8 2053.78   745.9 1986.86   826.6 1955.27   862.11935.804
   897.1 1925.56   977.11928.151  1068.5 1940.51    1129 1956.71  1169.3 1972.76
  1229.8 2010.16  1270.1 2041.25  1340.6 2080.87  1360.8  2097.1  1441.4 2138.54
  1481.8 2166.69  1552.3 2197.45  1784.2 2314.83  1864.8 2333.21  1905.1 2336.33
  2026.1 2334.59  2086.5 2328.77  2126.9 2331.66  2167.2 2337.92  2368.8 2386.23
#Mann= 3 , 0 , 0
       0     .08       0   862.1    .045       0   977.1     .08       0
Bank Sta=862.1,977.1
XS Rating Curve= 0 ,0
Exp/Cntr=0.3,0.1

Type RM Length L Ch R = 1 ,43679.7 ,1598.2,1602.4,1606.6
XS GIS Cut Line= 2
     2191481.967       334994.07     2193406.454      336546.075
#Sta/Elev= 30
       0 2460.44    70.6 2441.75   201.8 2370.86   232.1 2363.83   343.1 2295.72
   363.3 2289.38   383.5 2276.72   484.4 2200.66   504.6 2191.01   565.1 2148.97
   615.6 2119.72   867.8 1992.51   928.4 1966.82   988.9 1947.74  1078.41931.965
  1130.2 1925.57  1193.41926.576  1251.3 1930.06    1332    1985  1352.2 2003.55
  1422.8 2041.56    1443 2057.59  1523.8 2099.29  1634.8 2164.07  1725.6    2201
  1826.5 2233.01  2078.8 2298.11    2099 2307.08  2280.6 2349.51  2472.3  2383.5
#Mann= 3 , 0 , 0
       0     .08       0  1078.4    .045       0  1193.4     .08       0
Bank Sta=1078.4,1193.4
XS Rating Curve= 0 ,0
Exp/Cntr=0.3,0.1

Type RM Length L Ch R = 1 ,42077.2 ,1924.2,1949,1973.8
XS GIS Cut Line= 3
     2190651.644      336049.434     2192311.267      337966.801
     2193801.353      339872.135
#Sta/Elev= 30
       0 2347.29   201.3 2275.79   533.3 2056.98   815.1 1947.47   895.6 1929.67
  1216.71926.034  1247.8 1924.79  1331.7  1926.2  1469.2 1935.52  1861.6 2052.24
  2042.8 2050.28  2183.7 2071.64  2465.4 2210.94  2727.4 2218.47  2878.5  2281.1
  2979.3 2241.02    3201  2271.4  3271.6 2223.57  3463.1 2244.29  3523.6 2210.22
  3815.8 2245.09  3906.5  2172.2  3997.2 2129.45  4128.3 2158.64    4219 2145.59
  4319.8 2160.45  4501.2 2237.07  4672.5    2152  4833.7 2165.34  4954.7 2210.65
#Mann= 3 , 0 , 0
       0     .06       0  1216.7    .045       0  1331.7     .06       0
Bank Sta=1216.7,1331.7
XS Rating Curve= 0 ,0
Exp/Cntr=0.3,0.1

Type RM Length L Ch R = 1 ,40128.3 ,1194.4,1192.3,1190.2
XS GIS Cut Line= 3
     2190248.122      335808.873      2189164.09      338829.622
     2189838.519      340954.714
#Sta/Elev= 30
       0 2254.49   262.4 2190.41   504.6  2108.5   807.4 2066.58  1009.2 2061.84
  1180.8 1992.73    1312 1951.41  1372.6 1927.14  1418.41922.698  1533.41922.373
  1554.2 1922.37    2513 1925.14  2957.1 1932.57  3249.7 1941.01  3330.4 1959.97
  3834.8 1979.39  3935.7 1959.26  4097.2 1998.49  4278.7 2062.03  4500.7  2129.3
  4601.6 2177.51  4631.8  2197.7  4722.6 2227.24  4833.6 2238.97  4944.6 2241.19
  5035.4  2251.1  5176.6  2256.5  5237.2 2269.74  5358.2 2269.26  5438.9 2282.15
#Mann= 3 , 0 , 0
       0     .06       0  1418.4    .045       0  1533.4     .06       0
Bank Sta=1418.4,1533.4
XS Rating Curve= 0 ,0
Exp/Cntr=0.3,0.1

Type RM Length L Ch R = 1 ,38935.9 ,2127,2130.2,2133.4
XS GIS Cut Line= 2
     2189132.618      335675.883     2188022.934      339121.336
#Sta/Elev= 30
       0 2027.69    30.2 2021.21    70.6 2017.22   131.1 2005.26   151.2  2003.5
   191.6 1996.69     242 1985.04   302.5 1983.96   373.1 1978.02   433.6 1965.04
   473.9 1958.52   514.2 1943.81   544.5 1930.24   564.6 1927.69   756.2 1923.87
  1361.2 1924.34  1663.7 1919.57  1676.9 1919.57  1791.91920.163  1905.7 1922.72
  2268.6 1921.89  2409.8 1927.27  2692.1 1926.07  3317.3 1930.22  3337.4 1931.63
  3458.4 1948.19  3498.8 1947.99  3539.1  1953.2  3569.3 1958.73  3619.7 1970.43
#Mann= 3 , 0 , 0
       0     .06       0  1676.9    .045       0  1791.9     .06       0
Bank Sta=1676.9,1791.9
XS Rating Curve= 0 ,0
Exp/Cntr=0.3,0.1

Type RM Length L Ch R = 1 ,36805.7 ,1859.9,1857.2,1854.4
XS GIS Cut Line= 2
     2188047.298      334825.245     2186431.658      338006.037
#Sta/Elev= 30
       0 2034.35   100.8 2013.94   211.6 1986.53   302.3 1955.47   322.5 1951.29
   362.8 1935.91     393 1927.54   503.9  1923.9  1350.4 1925.32  1629.31911.795
  1662.9 1911.27  1744.31911.298  2620.3  1912.2    2711 1926.27  2781.5 1934.42
  2852.1 1949.56  2892.4 1964.26  2912.5  1977.4  2952.8 1995.89  3033.5 2014.32
  3083.8 2021.66  3093.9 2020.09    3104 2022.38  3174.6  2046.3  3265.3 2072.38
  3295.5 2083.98  3315.6 2086.23    3497 2075.13  3537.4 2075.63  3567.6  2081.7
#Mann= 3 , 0 , 0
       0     .06       0  1629.3    .045       0  1744.3     .06       0
#XS Ineff= 2 , 0
          1315.7 1925.47
Permanent Ineff=
       F       F
Bank Sta=1629.3,1744.3
XS Rating Curve= 0 ,0
Exp/Cntr=0.3,0.1

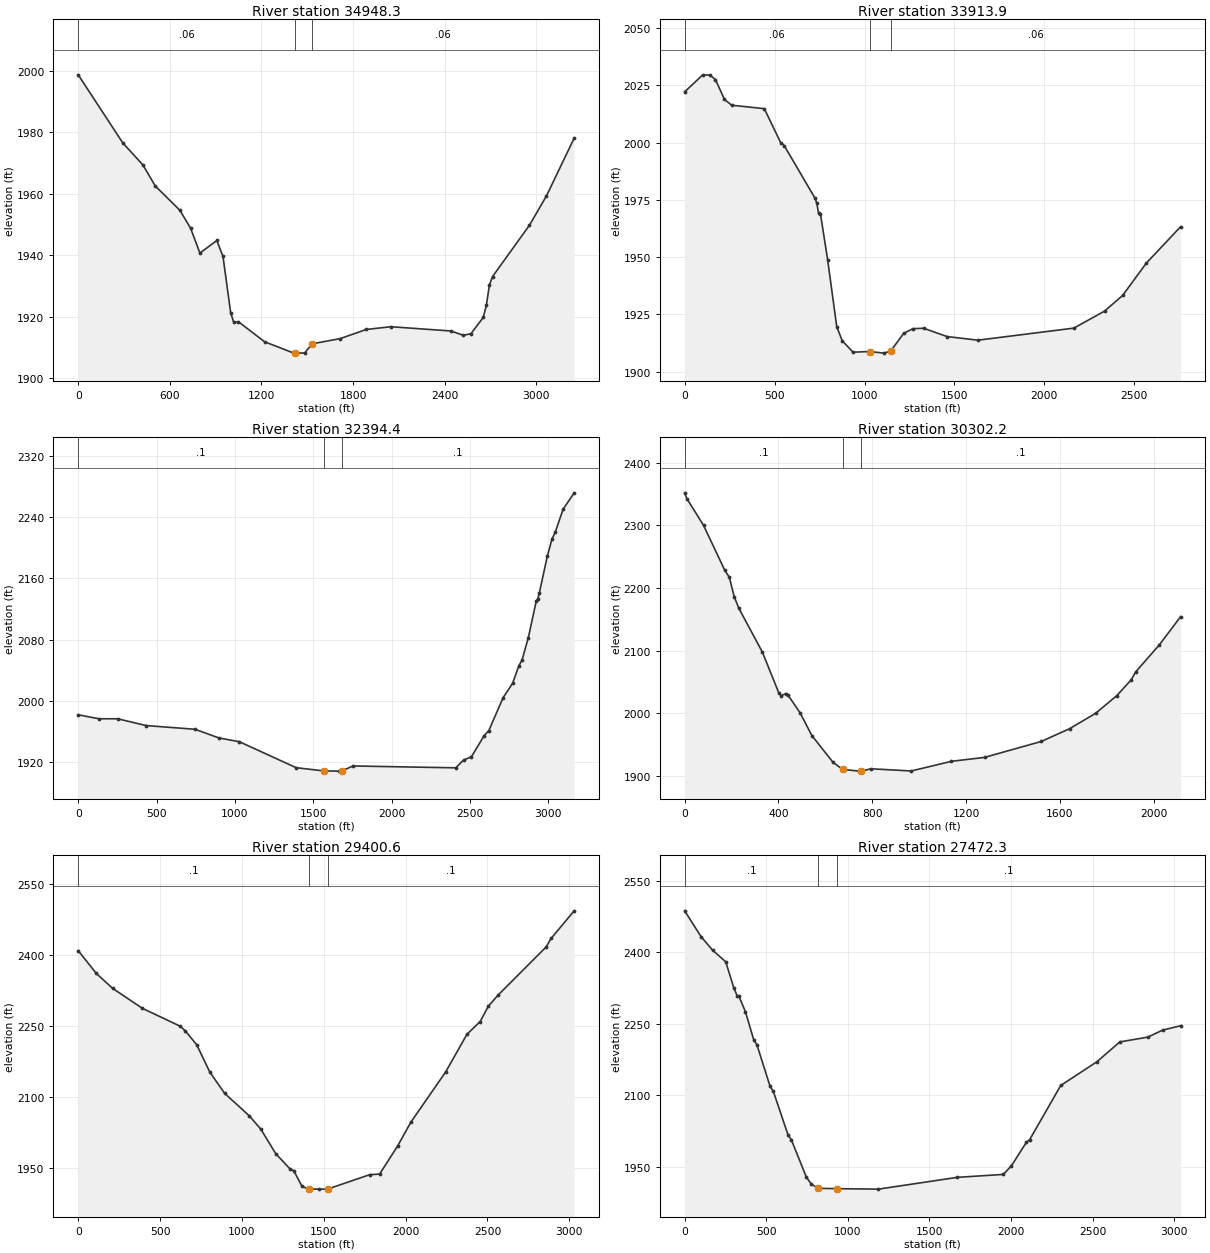
Type RM Length L Ch R = 1 ,34948.3 ,1035.2,1034.5,1033.7
XS GIS Cut Line= 2
     2186199.409      334451.629     2185230.025      337551.638
#Sta/Elev= 30
       0 1998.63   292.5 1976.46   423.7 1969.35   504.4 1962.51   665.8  1954.6
   736.4 1948.73   796.9 1940.69   907.8 1944.78   948.2 1939.59   998.6 1921.28
  1018.8 1918.15  1049.1 1918.38  1220.5 1911.87  1412.2 1908.17  1417.2 1908.17
  1482.8 1908.21  1532.21911.203  1714.8 1912.87  1886.3 1915.86  2047.7 1916.75
  2441.1 1915.37  2521.8 1913.97  2572.2 1914.48  2652.9 1919.79  2673.1 1923.72
  2693.2 1930.38  2713.4 1933.05  2955.5 1949.76  3066.5 1959.26    3248 1978.03
#Mann= 3 , 0 , 0
       0     .06       0  1417.2    .045       0  1532.2     .06       0
Bank Sta=1417.2,1532.2
XS Rating Curve= 0 ,0
Exp/Cntr=0.3,0.1

Type RM Length L Ch R = 1 ,33913.9 ,1518.2,1519.4,1520.5
XS GIS Cut Line= 2
     2185068.461      334693.975     2184361.619      337359.781
#Sta/Elev= 30
       0 2022.15   100.6 2029.56   140.9 2029.43   171.1 2027.49   221.4 2018.81
   261.7  2016.3   442.9 2014.79   533.5 2000.02   553.6 1998.67   724.7 1975.73
   734.8 1973.57   744.8 1969.12   754.9 1968.97   795.2  1948.8   845.5 1919.72
   875.7 1913.59   936.1 1908.55  1029.8 1908.84  1107.2 1908.14  1144.81908.972
  1217.9 1916.75  1268.2 1918.79  1328.6    1919  1459.5 1915.36  1630.6 1913.79
  2164.1 1919.05  2335.2 1926.48  2435.8 1933.33  2566.7 1947.36  2757.9  1963.3
#Mann= 3 , 0 , 0
       0     .06       0  1029.8    .045       0  1144.8     .06       0
Bank Sta=1029.8,1144.8
XS Rating Curve= 0 ,0
Exp/Cntr=0.3,0.1

Type RM Length L Ch R = 1 ,32394.4 ,2123.8,2092.2,2059.7
XS GIS Cut Line= 2
     2183796.145      334158.794     2182816.663      337167.923
#Sta/Elev= 30
       0 1981.82     131 1976.58     252 1976.56   433.4 1967.71   745.8 1962.85
     897 1951.56    1028 1946.61  1390.8 1912.66  1566.61908.483  1662.9 1908.18
  1681.61908.432  1753.6 1914.92  2408.7 1912.49  2459.1 1922.61  2509.4 1927.09
  2590.1 1954.51  2620.3 1961.23    2711  2004.1  2771.5 2022.78  2811.8 2045.91
    2832 2053.15  2872.3 2082.64  2922.6 2130.33  2932.7 2133.32  2942.8 2141.41
  2993.2 2188.96  3023.4  2211.5  3043.6 2220.18    3094 2250.32  3164.5 2271.76
#Mann= 3 , 0 , 0
       0      .1       0  1566.6    .045       0  1681.6      .1       0
Bank Sta=1566.6,1681.6
XS Rating Curve= 0 ,0
Exp/Cntr=0.3,0.1

Type RM Length L Ch R = 1 ,30302.2 ,887,901.6,916
XS GIS Cut Line= 4
     2181271.707      335107.982     2181434.588      335572.256
     2182142.244      336001.184     2182584.415      336663.036
#Sta/Elev= 30
       0 2352.03      10 2342.33    80.3 2300.25   170.7  2228.6   190.8 2217.02
   210.9  2186.5     231 2167.73   331.4 2097.72   401.6 2032.52   411.7 2028.15
   431.8 2031.58   441.8 2028.51     492 2000.94   542.5 1964.49   633.3 1921.57
   673.7 1910.49   744.3 1907.68   752.81907.697   794.8 1911.42   966.3 1907.92
  1137.9 1923.34  1279.2 1929.62    1521 1955.03  1641.9 1975.48  1752.8 1999.92
  1843.4 2028.28  1903.9 2053.13    1924 2066.19  2024.8 2109.33  2115.5  2154.3
#Mann= 3 , 0 , 0
       0      .1       0   673.7    .045       0   752.8      .1       0
Bank Sta=673.7,752.8
XS Rating Curve= 0 ,0
Exp/Cntr=0.3,0.1

Type RM Length L Ch R = 1 ,29400.6 ,1911.9,1928.2,1944.8
XS GIS Cut Line= 4
     2181029.361      334976.712     2181059.825      336252.818
     2181229.949      336662.663     2180645.647      337834.375
#Sta/Elev= 30
       0 2409.72   110.6 2361.37   211.1 2329.54     392 2287.43   623.2 2249.53
   653.3 2240.03   723.7 2210.38   804.1  2152.3   894.5 2107.34  1045.3  2059.7
  1115.7 2031.37  1206.1 1979.93  1296.6 1946.24  1316.8 1943.57  1367.2  1910.2
  1407.8 1904.69  1468.1 1904.49  1522.81904.496  1780.6 1935.09  1841.1 1936.32
  1951.9 1996.28  2032.4 2046.56    2244 2152.37  2374.9  2232.6  2455.4  2259.5
  2505.8 2292.22  2566.2 2315.98  2858.3 2417.44  2888.5  2435.4  3029.5 2493.98
#Mann= 3 , 0 , 0
       0      .1       0  1407.8    .045       0  1522.8      .1       0
Bank Sta=1407.8,1522.8
XS Rating Curve= 0 ,0
Exp/Cntr=0.3,0.1

Type RM Length L Ch R = 1 ,27472.3 ,1583.3,1584,1584.8
XS GIS Cut Line= 3
     2180342.714      334744.463     2179885.846      336235.898
     2179534.894      337672.811
#Sta/Elev= 30
       0 2486.99   100.6 2432.75   171.1 2404.36   251.6 2380.04   301.9 2324.36
     322 2308.51   332.1 2307.85   372.4 2275.11   422.7 2216.79   442.8  2205.8
   523.3 2118.65   543.4 2107.98     634 2016.09   654.1 2006.22   744.7 1928.92
   774.9 1913.82   818.11904.648   933.11903.926  1187.5 1902.98  1670.5  1927.7
  1952.3 1933.86  2002.6 1952.05  2093.1 2000.83  2113.3 2006.37  2304.4 2120.49
  2525.8 2170.18  2666.7 2211.97  2837.8  2221.9  2928.3 2236.66    3039 2245.89
#Mann= 3 , 0 , 0
       0      .1       0   818.1    .045       0   933.1      .1       0
Bank Sta=818.1,933.1
XS Rating Curve= 0 ,0
Exp/Cntr=0.3,0.1

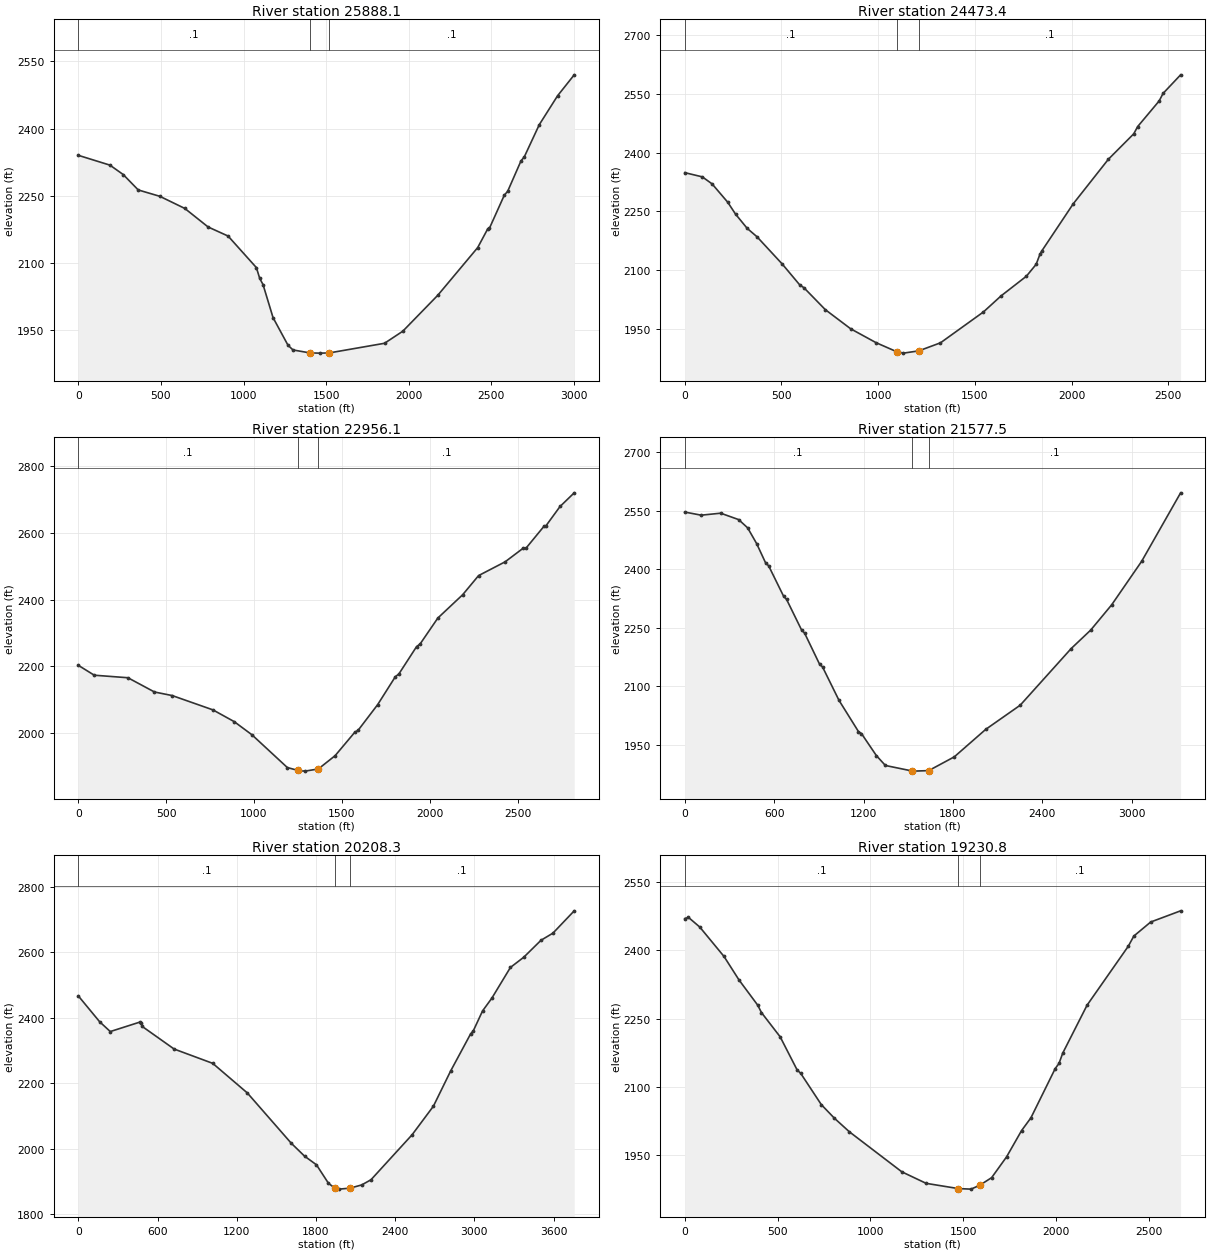
Type RM Length L Ch R = 1 ,25888.1 ,1406.9,1414.5,1422.1
XS GIS Cut Line= 2
      2178969.42      334108.305     2178080.818      336976.066
#Sta/Elev= 30
       0 2340.23   191.4 2318.33     272 2297.24   362.7 2262.92   493.7 2248.67
   644.8 2221.59   785.8  2180.2   906.7 2159.96    1078 2089.48  1098.2 2065.34
  1118.3 2051.52  1178.8 1977.85  1269.4 1916.09  1299.6 1905.58  1402.51898.968
  1460.8 1898.49  1517.51898.839  1853.8 1920.48  1964.6 1947.49  2176.2 2027.67
  2417.9 2134.18  2478.4 2175.84  2488.5 2176.97  2579.1 2251.33  2599.3 2259.84
  2679.9 2327.69    2700 2336.76  2790.7 2408.64  2901.5 2473.21  3002.3 2520.02
#Mann= 3 , 0 , 0
       0      .1       0  1402.5    .045       0  1517.5      .1       0
Bank Sta=1402.5,1517.5
XS Rating Curve= 0 ,0
Exp/Cntr=0.3,0.1

Type RM Length L Ch R = 1 ,24473.4 ,1519.5,1517.3,1515
XS GIS Cut Line= 2
     2178232.285      333946.741     2176686.613      335991.169
#Sta/Elev= 30
       0 2348.81    90.8 2338.05   141.3 2320.22     222 2273.66   262.4 2243.39
   322.9 2206.94   373.4  2185.7   504.5 2115.96   595.3 2062.61   615.5 2056.27
   726.5  2000.2   857.7 1951.46   988.9 1916.17  1094.51893.378  1130.1 1889.56
  1209.51895.283  1321.8 1915.79  1543.8 1994.31  1634.6 2035.05  1765.8 2085.25
  1816.3 2115.51  1836.4 2141.73  1846.6 2150.41    2008 2269.55  2189.6 2382.85
  2320.8 2447.64    2341 2466.04    2452 2531.19  2472.2 2550.37    2563 2597.69
#Mann= 3 , 0 , 0
       0      .1       0  1094.5    .045       0  1209.5      .1       0
Bank Sta=1094.5,1209.5
XS Rating Curve= 0 ,0
Exp/Cntr=0.3,0.1

Type RM Length L Ch R = 1 ,22956.1 ,1376.8,1378.5,1380.1
XS GIS Cut Line= 2
     2176970.066      332906.673     2175505.892      335320.035
#Sta/Elev= 30
       0  2202.7    90.7 2173.08   282.3 2165.46   433.5 2122.69   534.3 2112.01
   766.2 2069.07   887.2 2033.83     988 1994.44  1189.6  1896.1  1251.11887.237
  1290.4 1885.29  1366.11891.775  1461.8  1931.7  1572.7  2001.3  1592.9 2007.96
  1703.8  2084.7  1804.6  2168.6  1824.7  2176.9  1925.5 2258.91  1945.7 2266.92
  2046.5 2344.62  2187.7 2414.47  2278.4 2471.95  2429.6 2513.31  2530.4 2553.39
  2550.6 2555.68  2651.4  2620.3  2661.5    2621  2742.1 2679.27  2822.8 2720.28
#Mann= 3 , 0 , 0
       0      .1       0  1251.1    .045       0  1366.1      .1       0
Bank Sta=1251.1,1366.1
XS Rating Curve= 0 ,0
Exp/Cntr=0.3,0.1

Type RM Length L Ch R = 1 ,21577.5 ,1364.2,1369.2,1374.3
XS GIS Cut Line= 3
     2176051.171       332068.56     2174910.572      333736.315
     2173812.292      334446.726
#Sta/Elev= 30
       0 2546.53   110.6  2538.5   241.2 2543.62   361.9 2527.16   422.2 2506.03
   482.5  2465.7   542.8 2416.19   562.9 2408.81   663.4 2330.77   683.6 2322.46
   784.1 2244.17   804.2  2236.3   904.7 2156.58   924.8 2149.38  1035.4 2063.62
    1166 1983.58  1186.2 1978.42  1286.7 1921.72    1347 1896.55  1522.7 1882.72
    1538 1882.07  1637.71883.413  1809.4 1918.72  2020.5 1989.24  2251.9 2051.19
    2594 2196.48  2724.8 2243.76  2865.7  2308.6  3066.9 2420.15  3328.5 2595.83
#Mann= 3 , 0 , 0
       0      .1       0  1522.7    .045       0  1637.7      .1       0
Bank Sta=1522.7,1637.7
XS Rating Curve= 0 ,0
Exp/Cntr=0.3,0.1

Type RM Length L Ch R = 1 ,20208.3 ,979.9,977.5,975.2
XS GIS Cut Line= 3
     2175942.856      331879.036      2174350.42      332359.109
     2172829.136      333797.144
#Sta/Elev= 30
       0 2466.98   161.3 2388.15   241.9 2358.11   463.7 2386.72   473.8 2384.89
   483.8 2373.79   725.8 2304.67  1018.1 2260.95  1280.2 2170.52  1612.8 2016.97
  1713.6 1977.46  1804.1 1950.87  1894.7 1894.56  1943.71879.358  1975.2 1876.59
  2058.7 1879.61  2146.3 1889.39  2216.8 1905.14  2528.8 2042.88  2689.8    2130
  2820.6 2237.71  2971.6 2350.88  2991.7 2360.01  3062.2 2421.18  3132.6  2460.2
  3273.5 2554.13  3374.2 2585.18    3505 2637.09  3595.6 2658.92  3756.6 2727.05
#Mann= 3 , 0 , 0
       0      .1       0  1943.7    .045       0  2058.7      .1       0
Bank Sta=1943.7,2058.7
XS Rating Curve= 0 ,0
Exp/Cntr=0.3,0.1

Type RM Length L Ch R = 1 ,19230.8 ,1584.8,1562.9,1541.1
XS GIS Cut Line= 2
     2174526.056      330684.709     2172769.693      332698.672
#Sta/Elev= 30
       0 2469.57    20.2  2472.1    80.7 2451.11   211.8 2386.35   292.4 2334.85
   393.3 2279.48   413.4 2263.26   514.3 2209.94     605 2137.79   625.2 2129.65
   736.1 2061.11   806.7 2031.23   887.4 2001.44  1169.7 1913.67  1300.8 1888.36
    14751876.805  1542.8 1875.66    15901884.222  1653.8 1900.87  1734.4 1946.56
  1815.1 2004.18  1865.5 2032.19  1996.6 2140.45  2016.8 2151.48    2037 2174.27
    2168 2279.39  2389.9 2408.68  2420.1 2431.19  2510.9 2462.01  2672.2 2486.58
#Mann= 3 , 0 , 0
       0      .1       0    1475    .045       0    1590      .1       0
Bank Sta=1475,1590
XS Rating Curve= 0 ,0
Exp/Cntr=0.3,0.1