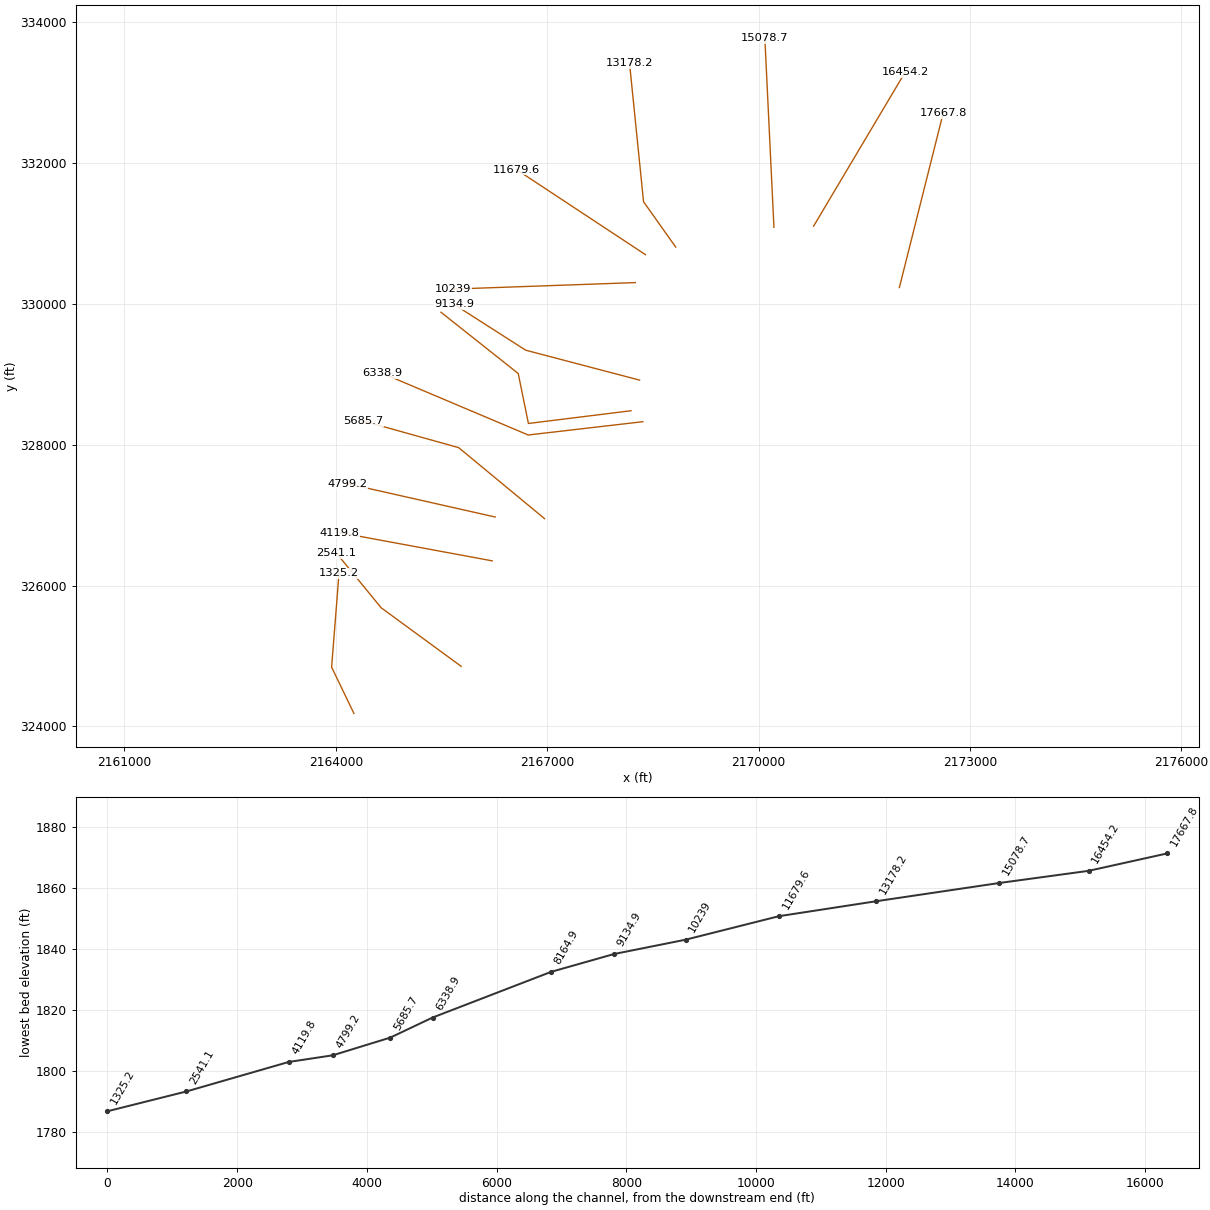
HEC-RAS study AntCk.prj: AntCk

--- AntCk.g01 (geometry) --- (continued)

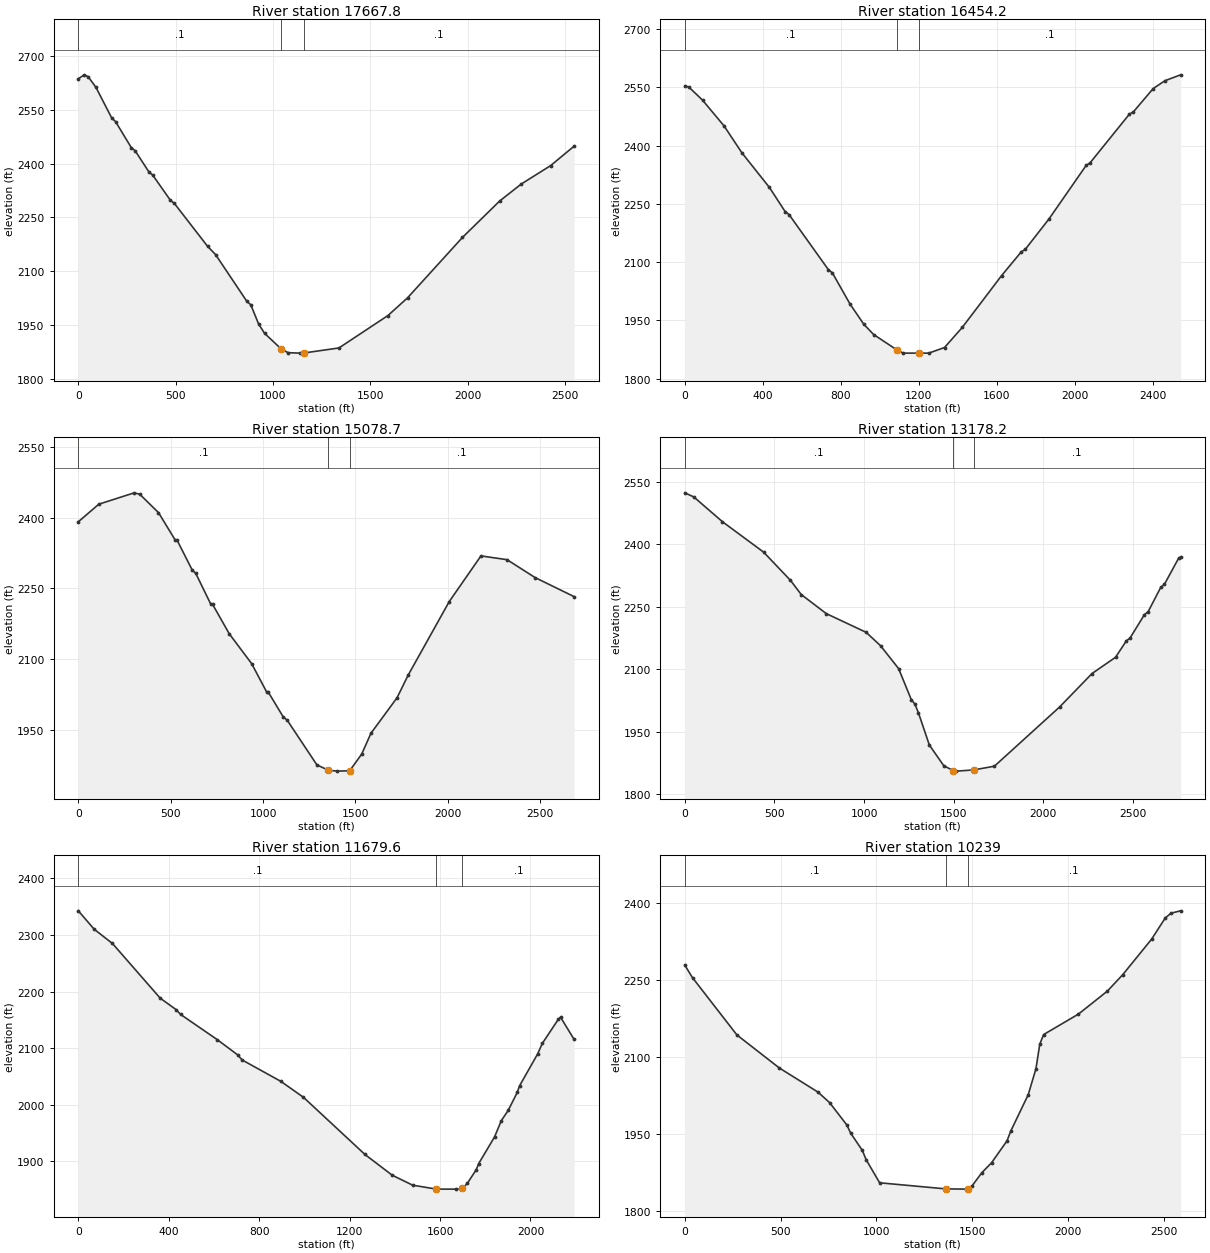
Type RM Length L Ch R = 1 ,17667.8 ,1220.1,1213.6,1207
XS GIS Cut Line= 2
     2171996.893      330228.054     2172617.474      332698.672
#Sta/Elev= 30
       0 2636.26    30.2  2647.3    50.3 2642.21    90.6 2612.37   171.2 2527.26
   191.3 2516.78   271.8 2444.64     292 2435.55   362.5 2376.71   382.6 2367.42
   473.2 2297.35   493.4 2288.85   664.5 2168.85   704.8 2146.37   865.9 2015.72
     886 2006.29   926.3  1952.5   956.5 1926.83  1043.11882.652  1077.3 1872.69
  1137.8 1871.41  1158.11871.743  1339.1 1885.85  1590.8 1976.27  1691.5 2025.59
  1973.4 2193.91  2164.8 2295.59  2275.5 2342.76  2426.5 2394.21  2547.4 2448.51
#Mann= 3 , 0 , 0
       0      .1       0  1043.1    .045       0  1158.1      .1       0
Bank Sta=1043.1,1158.1
XS Rating Curve= 0 ,0
Exp/Cntr=0.3,0.1

Type RM Length L Ch R = 1 ,16454.2 ,1362,1375.5,1389
XS GIS Cut Line= 2
     2170779.983      331099.405     2172078.856      333284.127
#Sta/Elev= 30
       0 2553.22    20.2 2550.81    90.8 2516.98   201.7 2450.25   292.5 2381.44
   433.7 2292.23   514.4 2230.04   534.6 2222.19   736.3 2080.38   756.4 2072.41
   847.2 1991.86   917.8 1939.88   968.2 1913.49    10881873.716  1119.5  1865.7
    1203 1865.69  1250.7 1865.68  1331.4 1880.14  1422.1  1931.7  1623.8 2065.17
  1724.7 2126.28  1744.9 2132.58  1865.9 2210.38  2057.5 2348.85  2077.7  2355.6
  2279.4 2480.99  2299.6 2486.71  2400.5 2546.42    2461 2566.85  2541.7 2582.06
#Mann= 3 , 0 , 0
       0      .1       0    1088    .045       0    1203      .1       0
Bank Sta=1088,1203
XS Rating Curve= 0 ,0
Exp/Cntr=0.3,0.1

Type RM Length L Ch R = 1 ,15078.7 ,1899.2,1900.5,1901.8
XS GIS Cut Line= 2
     2170217.111      331082.818     2170088.311        333764.2
#Sta/Elev= 30
       0 2391.09     111 2428.42   302.8 2452.53     333 2449.38     434 2410.53
   524.8 2352.16   534.9 2351.76   615.6 2289.38   635.8 2281.53   716.5 2216.66
   726.6 2215.89   817.4 2153.16   938.6 2089.78  1019.3 2029.89  1029.4 2028.81
  1110.1 1976.31  1130.3 1970.15  1291.8 1874.84  1354.21863.557  1402.8 1861.69
  1469.21862.502    1534 1897.72  1584.4 1942.11  1725.7 2017.53  1786.3 2065.84
  2008.3 2221.75  2179.9 2318.62  2321.2 2310.59  2472.5 2272.72  2684.5 2232.09
#Mann= 3 , 0 , 0
       0      .1       0  1354.2    .045       0  1469.2      .1       0
Bank Sta=1354.2,1469.2
XS Rating Curve= 0 ,0
Exp/Cntr=0.3,0.1

Type RM Length L Ch R = 1 ,13178.2 ,1478.4,1498.4,1518.5
XS GIS Cut Line= 3
     2168823.729        330801.8     2168367.074        331445.8
      2168168.02      333412.927
#Sta/Elev= 30
       0 2522.91      50 2513.13   209.9  2453.7   439.7 2380.76   589.6 2313.08
   649.6 2279.13   789.5 2233.32  1011.4 2188.59  1092.1 2156.44    1193 2101.52
  1263.6 2027.28  1283.8 2016.54  1303.9 1995.22  1364.5 1918.31  1445.2 1868.51
  1497.51857.177  1515.8 1855.69  1612.51858.583  1727.6 1867.52  2090.8 2009.26
  2272.4 2089.71  2403.5 2128.65    2464  2168.1  2484.2 2174.63  2564.9 2231.06
  2585.1  2237.8  2655.7 2296.24  2675.9 2303.34  2756.6 2367.05  2766.6 2368.84
#Mann= 3 , 0 , 0
       0      .1       0  1497.5    .045       0  1612.5      .1       0
Bank Sta=1497.5,1612.5
XS Rating Curve= 0 ,0
Exp/Cntr=0.3,0.1

Type RM Length L Ch R = 1 ,11679.6 ,1426.6,1440.5,1454.4
XS GIS Cut Line= 2
     2168394.696      330694.776     2166563.874      331902.454
#Sta/Elev= 30
       0 2342.75    70.4 2310.09   150.9 2285.04   362.2 2188.36   432.6 2168.06
   452.7 2159.52   613.7 2115.28   704.3 2088.26   724.4 2079.15   895.4 2041.42
     996 2013.05  1267.7 1912.11  1388.4  1875.4  1478.9 1857.77  1584.1 1850.79
  1670.1 1850.78  1699.1  1852.1  1720.4 1860.76  1760.6 1885.39  1770.7  1895.7
  1841.1 1943.04  1871.3 1971.98  1901.5 1989.94  1941.7 2021.84  1951.8 2033.38
  2032.3 2090.14  2052.4 2108.35  2122.8 2150.69  2132.9 2154.81  2193.3 2115.29
#Mann= 3 , 0 , 0
       0      .1       0  1584.1    .045       0  1699.1      .1       0
Bank Sta=1584.1,1699.1
XS Rating Curve= 0 ,0
Exp/Cntr=0.3,0.1

Type RM Length L Ch R = 1 ,10239   ,1110.4,1104,1097.6
XS GIS Cut Line= 2
     2168249.983      330298.309     2165662.485      330206.492
#Sta/Elev= 30
       0 2278.99    40.3  2254.6     272 2143.21   493.6 2078.89   695.1 2032.01
   755.6 2011.67   846.2 1967.93   866.4 1951.88   926.8 1918.62     947 1900.29
  1017.5 1855.38  1361.7 1843.54  1470.9 1843.05  1476.71843.386  1501.1 1849.89
  1551.5 1875.21  1601.8 1894.38  1682.4 1936.96  1702.6 1956.49  1793.2 2026.78
  1833.6 2077.38  1853.7 2125.24  1873.8 2143.95  2055.2 2183.68  2206.3 2228.41
  2286.9 2260.52    2438 2329.84  2508.5 2370.66  2538.8 2380.24  2589.1 2384.79
#Mann= 3 , 0 , 0
       0      .1       0  1361.7    .045       0  1476.7      .1       0
Bank Sta=1361.7,1476.7
XS Rating Curve= 0 ,0
Exp/Cntr=0.3,0.1

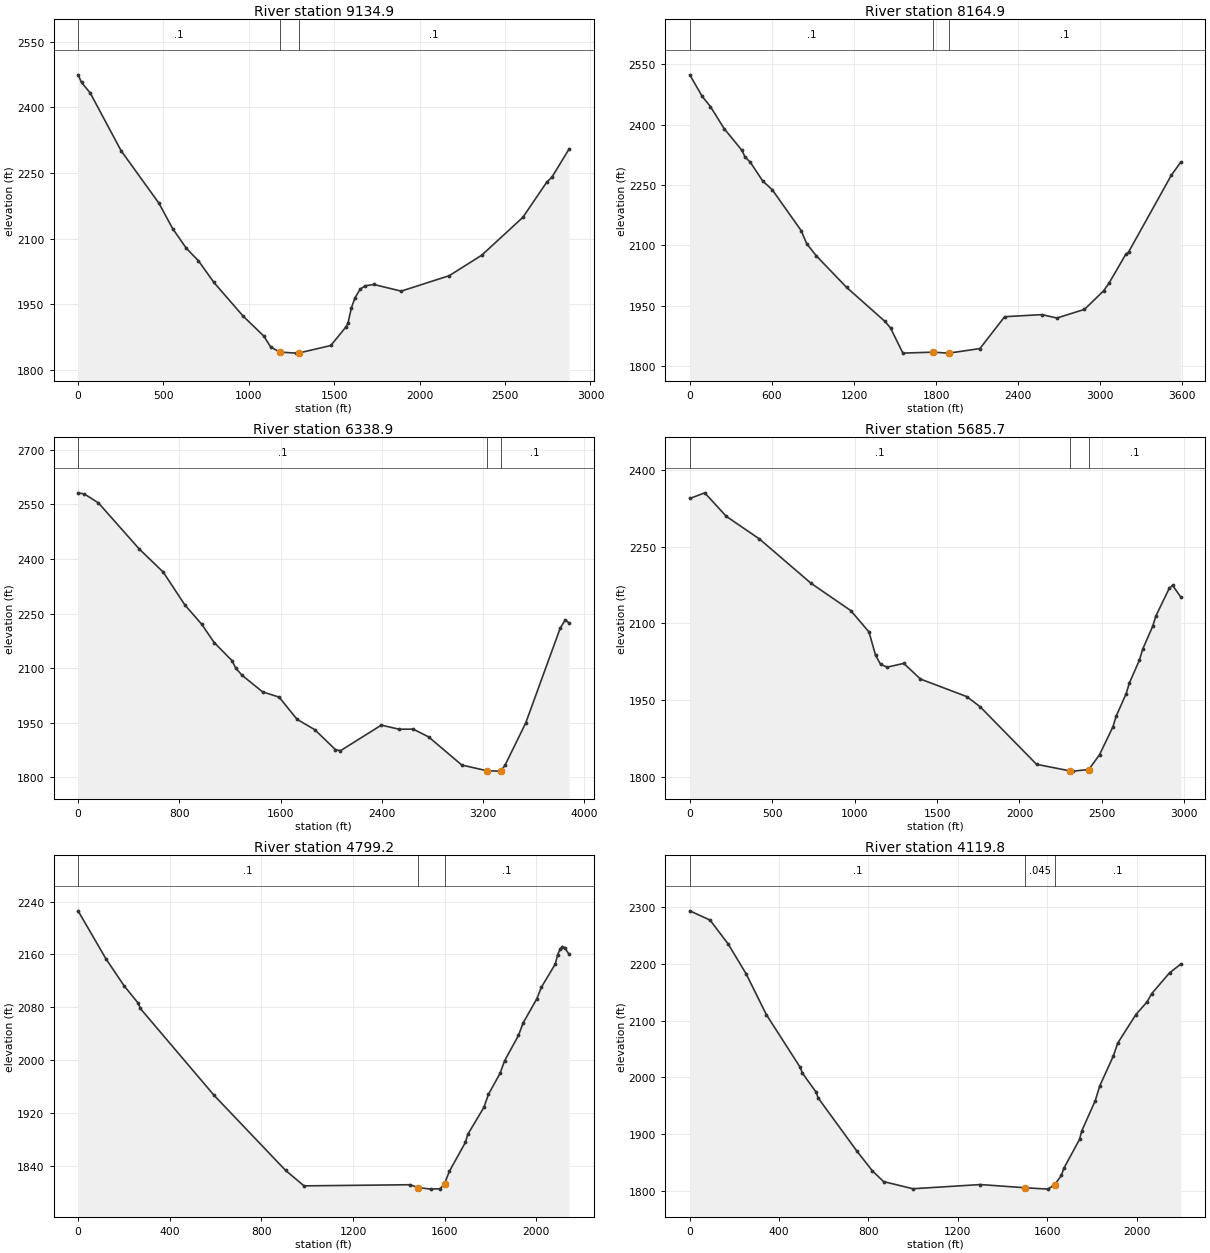
Type RM Length L Ch R = 1 ,9134.9  ,987.6,970,952.3
XS GIS Cut Line= 3
     2168310.943       328914.68     2166694.793      329339.362
     2165680.276      329988.181
#Sta/Elev= 30
       0  2474.7    20.1 2457.24    70.5 2433.58   251.7 2301.27   473.1 2181.24
   553.6  2123.1   634.2 2077.88   704.6 2049.61   795.2 2000.02   966.4 1922.98
  1087.2 1877.44  1127.4 1852.64  1180.31840.735  1278.4 1838.34  1295.31838.904
  1479.8  1855.8  1570.4 1899.21  1580.4 1907.33  1600.6 1942.13  1620.7 1964.44
  1650.9 1984.28    1681  1992.3  1731.2 1995.32  1891.8  1980.1  2172.8 2015.37
  2363.5 2062.25  2604.3 2148.84  2744.8 2229.68  2774.9 2240.96  2875.3 2305.46
#Mann= 3 , 0 , 0
       0      .1       0  1180.3    .045       0  1295.3      .1       0
Bank Sta=1180.3,1295.3
XS Rating Curve= 0 ,0
Exp/Cntr=0.3,0.1

Type RM Length L Ch R = 1 ,8164.9  ,1812.2,1825.9,1839.6
XS GIS Cut Line= 4
     2168189.626       328480.12     2166733.534      328299.661
     2166588.801      329008.852     2165492.657      329877.883
#Sta/Elev= 30
       0 2523.66    90.4 2470.25   150.7 2444.94   251.2    2390   381.9  2335.8
     402 2320.59   442.2 2306.66   532.6 2260.21     603 2238.12     814 2136.84
   854.2 2104.46   924.6 2074.18  1145.6 1996.03    1427 1911.13  1467.2 1895.07
  1557.7 1832.54  1778.61834.927  1889.4 1832.48  1893.6 1832.48  2120.7 1843.79
  2301.7 1922.93  2573.5 1928.12  2684.2 1919.72  2885.4 1941.17  3026.3 1987.68
  3066.6  2007.3  3187.3  2078.1  3207.5 2083.43  3519.4 2273.86  3589.9  2307.2
#Mann= 3 , 0 , 0
       0      .1       0  1778.6    .045       0  1893.6      .1       0
Bank Sta=1778.6,1893.6
XS Rating Curve= 0 ,0
Exp/Cntr=0.3,0.1

Type RM Length L Ch R = 1 ,6338.9  ,650.3,653.2,656.1
XS GIS Cut Line= 3
     2168358.129      328324.845     2166730.183      328136.097
     2164665.759      329009.054
#Sta/Elev= 30
       0 2581.91    50.3 2578.58   160.9  2554.2   482.6 2427.87   673.6  2363.8
   844.6  2273.5   975.3 2221.65  1075.8 2170.52  1216.6 2120.84  1246.7 2099.77
    1297 2080.46  1457.9 2035.16  1588.6 2020.74  1729.7 1959.93  1871.1 1931.12
  2032.6 1876.84    2073 1873.48  2396.1 1943.83  2537.4 1932.53  2648.5 1932.89
  2769.6 1911.54  3032.2 1834.21  3228.41818.687    3325 1817.48  3343.41818.641
  3375.4 1835.06    3537 1949.59  3809.6 2210.18    3850 2233.23  3880.3 2224.18
#Mann= 3 , 0 , 0
       0      .1       0  3228.4    .045       0  3343.4      .1       0
Bank Sta=3228.4,3343.4
XS Rating Curve= 0 ,0
Exp/Cntr=0.3,0.1

Type RM Length L Ch R = 1 ,5685.7  ,885.3,886.5,887.6
XS GIS Cut Line= 3
     2166961.983      326949.509     2165744.238       327956.49
     2164396.886        328332.9
#Sta/Elev= 30
       0 2344.13    90.6 2355.21   221.4 2309.21   422.7 2264.91   734.7 2178.49
   976.3 2124.95    1087 2083.16  1127.2 2037.25  1157.4 2019.67  1197.7 2014.32
  1298.4 2021.64    1399    1991  1680.8 1956.61  1761.3 1936.81  2103.5 1824.23
  2305.71811.344  2324.9 1810.88  2420.71814.015    2486 1843.25  2566.5 1897.22
  2586.6 1918.39    2647 1962.28  2667.1 1983.55  2727.5 2027.86  2747.6 2049.48
    2808 2094.07  2828.1 2114.73  2908.7 2168.52  2928.8  2174.3  2979.1    2151
#Mann= 3 , 0 , 0
       0      .1       0  2305.7    .045       0  2420.7      .1       0
Bank Sta=2305.7,2420.7
XS Rating Curve= 0 ,0
Exp/Cntr=0.3,0.1

Type RM Length L Ch R = 1 ,4799.2  ,678.5,679.4,680.3
XS GIS Cut Line= 2
     2166262.764       326972.16     2164171.859      327443.851
#Sta/Elev= 30
       0 2225.98   120.8 2153.84   201.3 2112.39   261.6 2086.67   271.7 2078.28
   593.7  1946.9   905.7 1833.41   986.2    1810  1449.1 1811.72  1484.41807.465
  1539.7 1805.07  1579.9 1805.69  1599.41813.046  1620.2 1831.77  1690.6 1875.75
  1700.7 1887.75  1771.1 1928.65  1791.2 1948.48  1841.6 1980.03  1861.7 1999.27
  1922.1 2037.44  1942.2 2056.18  2002.6 2093.16  2022.7 2110.72  2083.1 2145.66
  2093.1 2159.63  2103.2 2167.55  2113.3 2171.86  2123.3 2170.38  2143.4 2160.14
#Mann= 3 , 0 , 0
       0      .1       0  1484.4    .045       0  1599.4      .1       0
Bank Sta=1484.4,1599.4
XS Rating Curve= 0 ,0
Exp/Cntr=0.3,0.1

Type RM Length L Ch R = 1 ,4119.8  ,1589.7,1578.7,1567.7
XS GIS Cut Line= 2
     2166219.903      326350.254     2164058.129      326750.454
#Sta/Elev= 30
       0 2293.44    90.8 2277.08   171.4 2235.16   252.1 2182.45   342.9 2110.36
   494.2 2017.59   504.2 2007.26   564.8 1974.24   574.8 1963.52   746.3 1870.84
   816.9 1835.29   867.3 1816.22   998.4 1803.56    1301 1810.94  1502.6 1805.28
  1603.1 1802.88  1633.8 1810.65    1664  1827.3  1674.1 1839.29  1744.7 1890.43
  1754.8 1905.45  1815.3 1958.93  1835.4 1984.91    1896 2037.42  1916.1 2060.49
  1996.8 2110.38  2047.2 2132.94  2067.4 2147.28  2148.1 2184.23  2198.5 2199.65
#Mann= 3 , 0 , 0
       0      .1       0  1502.6    .045       0  1633.8      .1       0
Bank Sta=1502.6,1633.8
XS Rating Curve= 0 ,0
Exp/Cntr=0.3,0.1

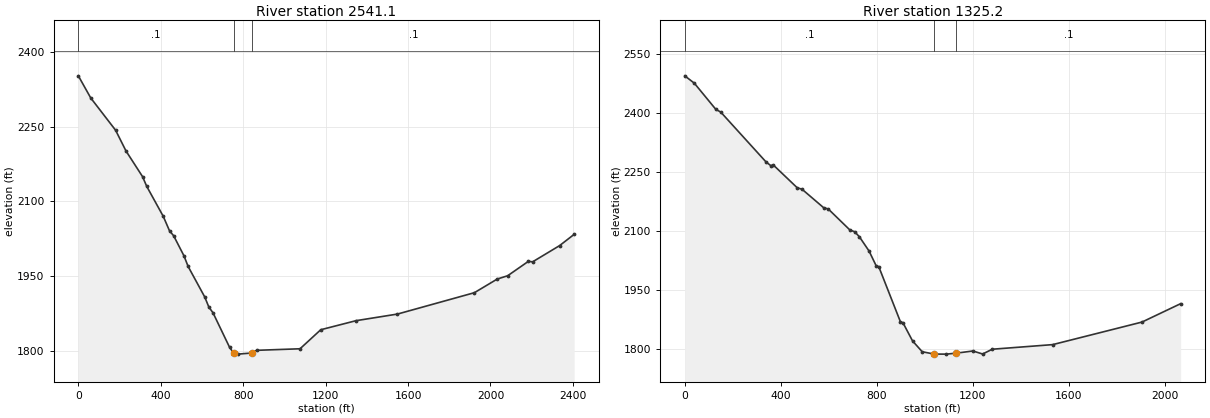
Type RM Length L Ch R = 1 ,2541.1  ,1239.4,1215.9,1192.5
XS GIS Cut Line= 3
     2165779.365      324853.581     2164643.583      325684.927
     2164011.292      326457.727
#Sta/Elev= 30
       0 2351.86    60.3 2307.38     181 2242.55   231.2 2201.07   311.7 2149.45
   331.8 2130.04   412.2  2069.7   442.4 2040.77   462.5 2030.83   512.7 1990.43
   532.8 1969.15   613.3 1907.96   633.4 1887.62   653.5 1876.16   733.9 1806.87
     754 1795.07   774.1 1793.18   844.5 1795.55   864.6 1800.81  1075.8 1803.93
  1176.3 1842.13  1347.2  1860.3  1548.7 1873.62  1921.9 1916.51  2032.8 1943.92
  2083.3  1950.5  2184.1  1979.5  2204.3 1978.41  2335.4 2011.04    2406 2033.62
#Mann= 3 , 0 , 0
       0      .1       0     754    .045       0   844.5      .1       0
Bank Sta=754,844.5
XS Rating Curve= 0 ,0
Exp/Cntr=0.3,0.1

Type RM Length L Ch R = 1 ,1325.2  ,1327,1325.1,1323.3
XS GIS Cut Line= 3
     2164257.183      324186.163     2163941.038      324841.872
      2164046.42      326176.709
#Sta/Elev= 30
       0  2494.1    39.9 2475.23   129.6 2408.68   149.6 2402.14     339 2274.95
     359 2265.61     369 2267.47   468.7 2209.51   488.6  2205.9   578.4 2159.08
   598.3 2155.49   688.1 2102.31     708 2097.82   727.9 2084.93   768.2 2048.66
   798.4 2010.42   808.5 2009.16   899.1 1868.51   909.2  1866.7   949.4 1820.24
   989.7 1792.74  1039.71786.832  1089.7 1786.69  1130.6 1789.05  1201.1 1794.69
  1241.4 1786.99  1281.7 1799.13  1533.4 1810.84  1905.8 1868.17  2066.9 1914.94
#Mann= 3 , 0 , 0
       0      .1       0  1039.7    .045       0  1130.6      .1       0
Bank Sta=1039.7,1130.6
XS Rating Curve= 0 ,0
Exp/Cntr=0.3,0.1

Chan Stop Cuts=-1
Use User Specified Reach Order=0
Composite Channel Slope=5